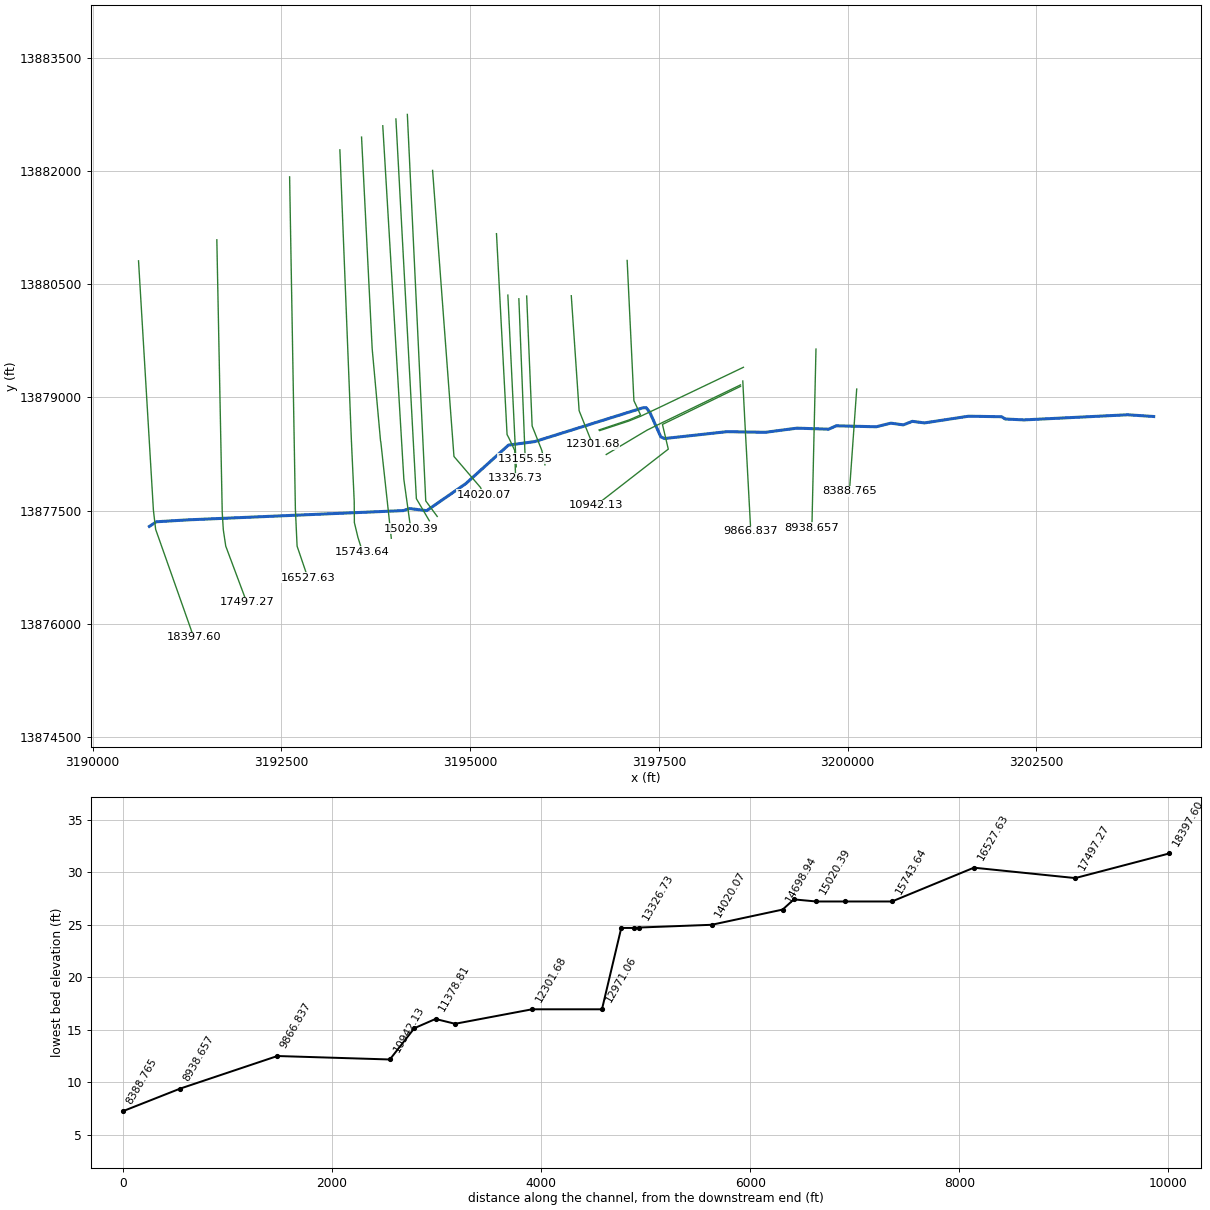
--- G103-07-00.prj (project) ---

Proj Title=G103-07-00
Current Plan=p02
Default Exp/Contr=.3,.1
English Units
Geom File=g01
Flow File=f01
Flow File=f02
Plan File=p01
Plan File=p02
Y Axis Title=Elevation
X Axis Title(PF)=Main Channel Distance
X Axis Title(XS)=Station
BEGIN DESCRIPTION:
HCFCD Watershed Unit ID: G
M3 Study Identifier: 2007_Effective_G
Engineer: HCFCD
Project Name: EffectiveFEMA Study for watershed San Jancinto River (G)
Study Completion Date: 6/18/2007
FEMA Case Number: [No Data]
FEMA Approval Date: [No Date in Database]
Vertical Datum: NAVD 1988
Datum Note: 2001 ADJ
HYDRAULICS
HCFCD Unit No.:  G103-07-00
Hydraulic Program Name: HEC-RAS
Hydraulic Program Version: 3.0.1
Steady Hydraulic Model: Yes
Unsteady Hydraulic Model: No
Update1:
The effective FEMA hydraulic model for unit number G103-07-00 has been updated by FEMA LOMR 13-06-4399P with an effective date of 6/26/2014.
END DESCRIPTION:
DSS Export Rating Curves= 0
DSS Export Rating Curve Sorted= 0
DSS Export Volume Flow Curves= 0
DXF OffsetX= 0
DXF OffsetY= 0
DXF ScaleX= 1
DXF ScaleY= 10

--- G103-07-00.p02 (plan) ---

Plan Title=Effective Floodway 2014
Version=Version 3.0.1  May 2012
Short Identifier=Prop FW
Geom File=g01
Flow File=f02
Subcritical Flow
K Sum by GR= 0
Std Step Tol= 0.01
Critical Tol= 0.01
Num of Std Step Trials= 20
Max Error Tol= 0.3
Flow Tol Ratio= 0.001
Split Flow NTrial= 30
Split Flow Tol= 0.02
Split Flow Ratio= 0.02
Log Output Level= 0
Friction Slope Method= 0
Unsteady Friction Slope Method= 2
Secant Critical Depth
Global Vel Dist= 0 , 0 , 0
Global Log Level= 0
CheckData=True
Encroach Param=-1 ,0,0, 2
Encroach River=G103-07-00
Encroach Reach=G103-07-00_0047
Encroach Node=18397.60
       1 3440.17 3506.13
Encroach Node=17497.27
       1 3931.96 4003.55
Encroach Node=16527.63
       1 4437.55  4515.9
Encroach Node=15743.64
       1 4766.57 4847.63
Encroach Node=15292.10
       1 4934.33 5015.31
Encroach Node=15020.39
       1 5135.46 5212.44
Encroach Node=14859.16
       4       1
Encroach Node=14805.76
       1 5210.22 5300.11
Encroach Node=14698.94
       1 5246.29 5339.68
Encroach Node=14020.07
       1 4111.56 4230.16
Encroach Node=13326.73
       1 2756.18 2867.58
Encroach Node=13281.37
       1  1914.7 2022.75
Encroach Node=13218.35
       1    1840    2030
Encroach Node=13155.55
       1 1856.33 1968.48
Encroach Node=12971.06
       1 1834.94 1990.28
Encroach Node=12301.68
       1 1664.68 1825.42
Encroach Node=11565.76
       1 1908.73 2060.83
Encroach Node=11378.81
       1 1310.17 1461.23
Encroach Node=11276.86
       1    1170 1446.92
Encroach Node=11176.29
       1 1178.29 1311.98
Encroach Node=10942.13
       1 1276.29  1383.9
Encroach Node=9866.837
       1  624.98  730.36
Encroach Node=8938.657
       1     984 1125.93
Encroach Node=8388.765
       1  423.57   553.9
Encroach Node=8249.040
       1  422.25  550.41
Encroach Node=8217.5
       1  449.42  530.68
Encroach Node=8186.531
       1  423.57   553.9
Encroach Node=8145.717
       1  421.38  555.89
Encroach Node=8122.57
       1  456.42  527.35
Encroach Node=8099.670
       1  422.97  555.97
Encroach Node=8056.477
       1  424.36   543.5
Encroach Node=8011.619
       1  459.76  529.56
Encroach Node=7966.656
       1  432.39  551.25
Encroach Node=7859.283
       1  415.12  539.48
Encroach Node=6885.989
       1  911.53 1070.83
Encroach Node=6073.299
       1    1390 1778.68
Encroach Node=5485.841
       1    1670 2760.92
Encroach Node=4726.477
       1    1120 1723.49
BEGIN DESCRIPTION:
FEMA Effective Floodway June 2007 + LOMR 13-06-4399P
END DESCRIPTION:
Computation Interval=1HOUR
Output Interval=1HOUR
Run HTab= 0
Run UNet= 0
Run PostProcess= 0
UNET Theta= 1
UNET ZTol= 0.02
UNET ZSATol= 0.1
UNET MxIter= 20
UNET MaxInSteps= 20
UNET DtIC= 0
UNET DtMin= 0
UNET MaxCRTS= 20
UNET WFStab= 2
UNET SFStab= 1
UNET WFX= 1
UNET SFX= 1
UNET Convert EG Bridges=-1
UNET Use Existing IB Tables=-1
Instantaneous Interval=1HOUR
Write IC File= 0
Write Velocity= 0
Write Detailed= 0

--- G103-07-00.p01 (plan) ---

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Plan Title=Effective Multi-Profile 2014
Short Identifier=Proposed MP
Geom File=g01
Flow File=f01
Encroach Param=-1 ,0,0, 0
FEMA Effective Multi-Profile June 2007 + LOMR 13-06-4399P
UNET ZSATol= 0.05
UNET MaxInSteps= 0
IC Time=0

--- G103-07-00.f02 (steady flow) ---

Flow Title=Effective Floodway 2014
Version=Version 3.0.1  Mar 2001
Number of Profiles= 2
Profile Names=1PCT_100yr, 1PCTFloodway_100yr
River Rch & RM=G103-07-00,G103-07-00_0047 ,18397.60
     558     558
River Rch & RM=G103-07-00,G103-07-00_0047 ,16527.63
     569     569
River Rch & RM=G103-07-00,G103-07-00_0047 ,15743.64
     674     674
River Rch & RM=G103-07-00,G103-07-00_0047 ,15292.10
     745     745
River Rch & RM=G103-07-00,G103-07-00_0047 ,15020.39
     840     840
River Rch & RM=G103-07-00,G103-07-00_0047 ,14698.94
    1081    1081
River Rch & RM=G103-07-00,G103-07-00_0047 ,14020.07
    3893    3893
River Rch & RM=G103-07-00,G103-07-00_0047 ,13326.73
    4057    4057
River Rch & RM=G103-07-00,G103-07-00_0047 ,12971.06
    4383    4383
River Rch & RM=G103-07-00,G103-07-00_0047 ,12301.68
    4770    4770
River Rch & RM=G103-07-00,G103-07-00_0047 ,11565.76
    5227    5227
River Rch & RM=G103-07-00,G103-07-00_0047 ,10942.13
    5408    5408
River Rch & RM=G103-07-00,G103-07-00_0047 ,9866.837
    5570    5570
River Rch & RM=G103-07-00,G103-07-00_0047 ,8938.657
    5765    5765
River Rch & RM=G103-07-00,G103-07-00_0047 ,7859.283
    5946    5946
River Rch & RM=G103-07-00,G103-07-00_0047 ,6885.989
    6146    6146
Boundary for River Rch & Prof#=G103-07-00,G103-07-00_0047 , 1
Up Type= 3
Up Slope=.0024
Dn Type= 3
Dn Slope=.0024
DSS Import GetInterval= 0
DSS Import GetPeak= 0
DSS Import FillOption= 0

--- G103-07-00.f01 (steady flow) ---

Flow Title=Effective Multi-Profile 2014
Version=Version 3.0.1  Mar 2001
Number of Profiles= 4
Profile Names=10PCT_10yr, 2PCT_50yr, 1PCT_100yr, 0.2PCT_500yr
River Rch & RM=G103-07-00,G103-07-00_0047 ,18397.60
     340     483     558     768
River Rch & RM=G103-07-00,G103-07-00_0047 ,16527.63
     346     492     569     783
River Rch & RM=G103-07-00,G103-07-00_0047 ,15743.64
     411     583     674     922
River Rch & RM=G103-07-00,G103-07-00_0047 ,15292.10
     457     645     745    1017
River Rch & RM=G103-07-00,G103-07-00_0047 ,15020.39
     516     727     840    1141
River Rch & RM=G103-07-00,G103-07-00_0047 ,14698.94
     669     938    1081    1458
River Rch & RM=G103-07-00,G103-07-00_0047 ,14020.07
    2346    3360    3893    5386
River Rch & RM=G103-07-00,G103-07-00_0047 ,13326.73
    2446    3501    4057    5622
River Rch & RM=G103-07-00,G103-07-00_0047 ,12971.06
    2646    3783    4383    6094
River Rch & RM=G103-07-00,G103-07-00_0047 ,12301.68
    2885    4120    4770    6659
River Rch & RM=G103-07-00,G103-07-00_0047 ,11565.76
    3160    4523    5227    7228
River Rch & RM=G103-07-00,G103-07-00_0047 ,10942.13
    3267    4679    5408    7482
River Rch & RM=G103-07-00,G103-07-00_0047 ,9866.837
    3361    4817    5570    7708
River Rch & RM=G103-07-00,G103-07-00_0047 ,8938.657
    3474    4983    5765    7980
River Rch & RM=G103-07-00,G103-07-00_0047 ,7859.283
    3579    5139    5946    8233
River Rch & RM=G103-07-00,G103-07-00_0047 ,6885.989
    3695    5310    6146    8550
Boundary for River Rch & Prof#=G103-07-00,G103-07-00_0047 , 1
Up Type= 3
Up Slope=.0024
Dn Type= 3
Dn Slope=.0024
DSS Import GetInterval= 0
DSS Import GetPeak= 0
DSS Import FillOption= 0

--- G103-07-00.g01 (geometry) ---

Geom Title=G103-07-00 2007
Version=Version 3.0.1  Mar 2001

River Reach=G103-07-00      ,G103-07-00_0047
Reach XY= 30
     3190751.716    13877291.533     3190844.072    13877352.707
        3191261.    13877378.001     3194117.499       13877501.
      3194197.75    13877528.001     3194424.999    13877499.999
     3194945.499       13877860.       3195507.5    13878368.001
     3195856.249    13878415.001        3197287.    13878862.001
     3197333.249    13878863.001      3197379.75    13878803.001
     3197525.499       13878478.     3197573.249       13878455.
       3198398.5    13878546.001      3198912.75       13878538.
     3199331.249       13878593.     3199748.249       13878579.
        3199849.    13878624.001      3200378.75       13878611.
     3200573.001    13878659.001        3200737.    13878636.001
     3200857.751    13878683.001     3201017.501    13878661.999
      3201601.75    13878750.999     3202040.251    13878744.001
       3202088.5    13878714.001     3202336.499    13878702.001
      3203709.75       13878770.     3204054.191       13878747.

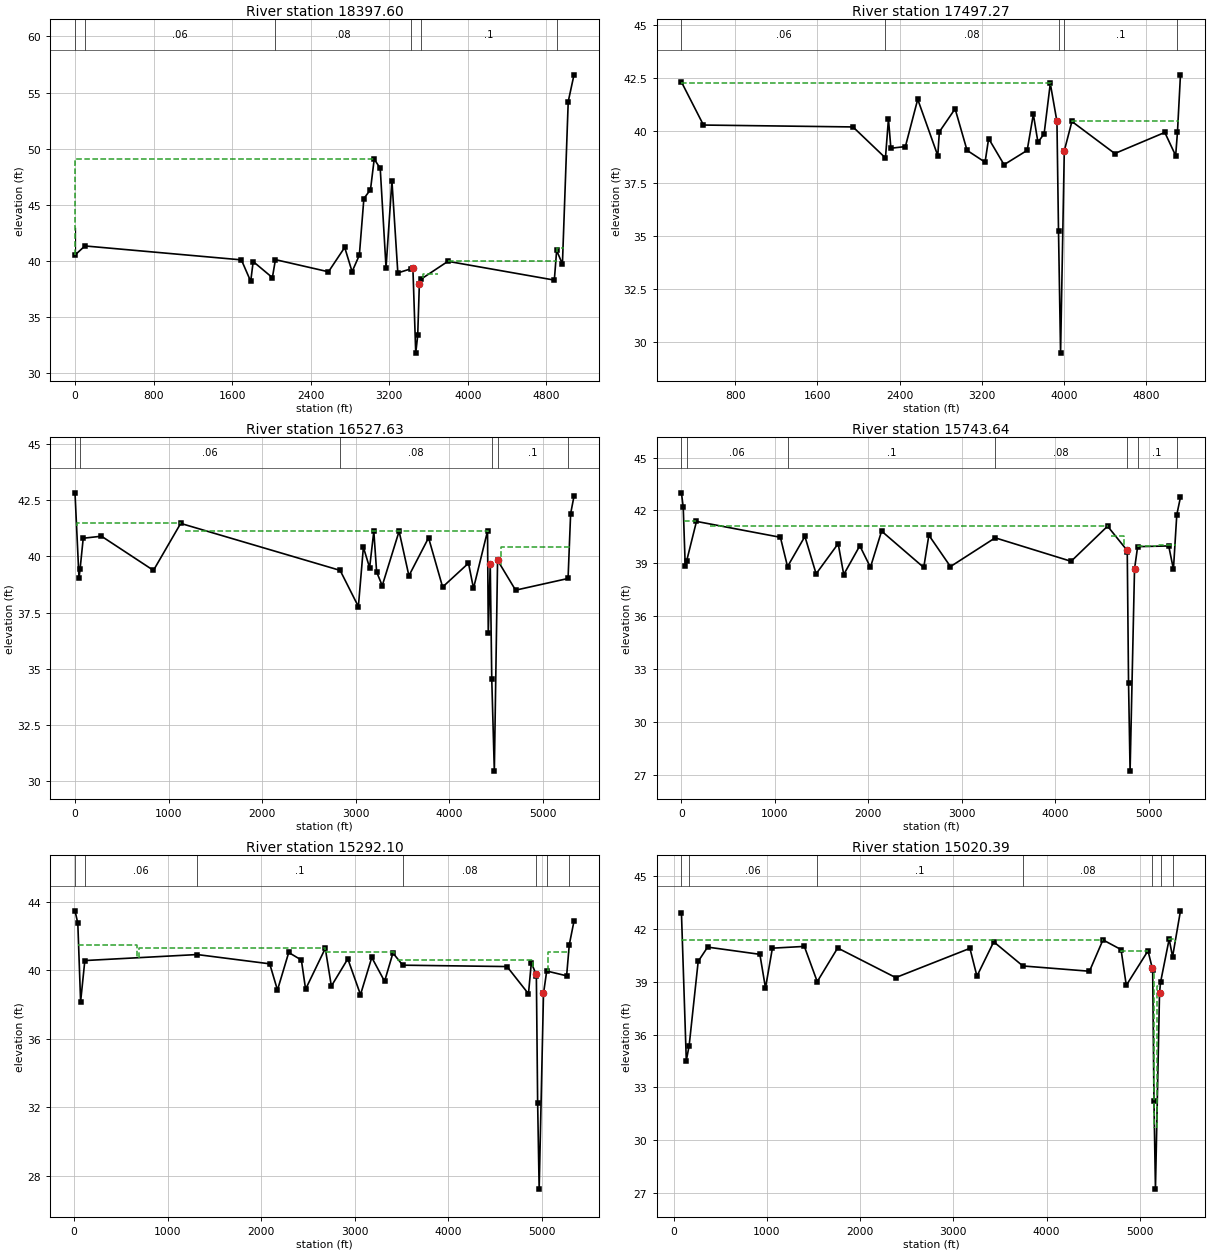
Type RM Length L Ch R = 1 ,18397.60,915.13,900.24,842.42
BEGIN DESCRIPTION:
Stations 3402.04-3538.52 developed from survey information, and the remainder developed from LiDAR
END DESCRIPTION:
XS GIS Cut Line= 5
     3190607.872    13880809.273      3190805.15    13877504.359
      3190834.72    13877252.705     3191298.076    13875939.868
 3191338.656977713875822.7067077
#Sta/Elev= 30
       0   40.54  101.21   41.35 1694.04   40.11 1788.93    38.2 1814.25   39.96
  2009.6   38.53 2040.74   40.13 2580.61   39.05 2745.91   41.22 2821.04   39.06
 2894.99   40.53 2941.25   45.57 3008.43   46.36 3046.44   49.08 3107.69   48.25
 3166.65   39.42 3226.76   47.14 3286.87   38.95 3418.24   39.31 3440.17   39.38
 3469.16   31.81 3489.19   33.39 3506.13      38 3520.28   38.38 3796.91   39.98
 4880.15   38.31 4903.67   40.95 4962.47   39.73  5021.6    54.2 5080.38   56.58
#Mann= 6 ,-1 , 0
       0     .03       0  101.21     .06       0 2040.74     .08       0
 3418.24     .04       0 3520.28      .1       0 4903.67     .03       0
#XS Ineff= 6 ,-1
   -2.14 3046.25   49.07 3108.96 3226.76   47.14 3797.43 4904.75   39.98
 4910.76 4981.44   41.17 3538.52    3700   38.86    3250 3440.17   39.38
Permanent Ineff=
       F       F       F       F       F       F
#Block Obstruct= 1 ,-1
       0       2      43
Bank Sta=3440.17,3506.13
XS Rating Curve= 0
Exp/Cntr=.3,.1

Type RM Length L Ch R = 1 ,17497.27,970.16,969.58,947.88
BEGIN DESCRIPTION:
Stations 3902.70-4044.20 developed from survey information, and the remainder developed from LiDAR
END DESCRIPTION:
XS GIS Cut Line= 5
 3191645.112031913881087.3295129     3191716.737    13877473.604
     3191731.123    13877244.467     3191763.333    13877029.733
 3192041.717678213876284.5102751
#Sta/Elev= 30
  277.55   42.31  491.67   40.27 1946.96   40.18 2263.08   38.71 2292.03   40.56
 2315.72   39.17 2457.06   39.25 2577.08   41.49 2772.12   38.82 2787.79   39.95
 2940.85   41.04 3057.18   39.07 3232.47   38.51 3267.22   39.63 3417.25   38.39
 3642.29   39.07  3702.3   40.78 3747.31   39.45 3807.32   39.86 3867.34   42.24
 3931.96   40.44 3947.23   35.26 3967.28   29.46 4003.55   39.05 4077.71   40.44
 4495.08   38.92  4981.7   39.92 5087.54   38.82 5105.08   39.94 5134.23   42.65
#Mann= 5 ,-1 , 0
  277.55     .06       0 2263.08     .08       0 3947.23     .04       0
 4003.55      .1       0 5105.08     .03       0
#XS Ineff= 2 ,-1
  241.94 3870.97   42.24 4077.59 5117.94   40.44
Permanent Ineff=
       F       F
Bank Sta=3931.96,4003.55
XS Rating Curve= 0
Exp/Cntr=.3,.1

Type RM Length L Ch R = 1 ,16527.63,778.67,784.19,802.66
BEGIN DESCRIPTION:
Stations 4416.37-4548.38 developed from survey information, and the remainder developed from LiDAR
END DESCRIPTION:
XS GIS Cut Line= 4
     3192609.146    13881921.179     3192685.531     13877522.47
     3192708.162    13877029.733 3192849.970468413876613.2467569
#Sta/Elev= 30
       0   42.83   42.94   39.03   54.32   39.43   87.95   40.81  282.97    40.9
  838.54   39.38 1129.46   41.47 2833.36   39.38 3028.39   37.77 3081.86   40.41
 3148.41    39.5 3193.41   41.12 3223.42   39.31 3283.43    38.7 3463.46   41.12
 3568.47   39.14  3778.5   40.83 3928.53   38.64 4205.05    39.7 4258.58   38.58
 4408.61   41.13 4416.37   36.59 4437.55   39.65 4453.85   34.53 4481.23   30.45
  4515.9   39.83  4708.4    38.5 5269.21   39.02 5296.52    41.9  5332.6   42.68
#Mann= 6 ,-1 , 0
       0     .03       0   54.32     .06       0 2833.36     .08       0
 4453.85     .04       0  4515.9      .1       0 5269.21     .03       0
#XS Ineff= 4 ,-1
   16.68 1129.58   41.47 1178.82 4408.66   41.13 4547.92 5291.31    40.4
    4409 4437.55   39.67
Permanent Ineff=
       F       F       F       F
Bank Sta=4437.55,4515.9
XS Rating Curve= 0
Exp/Cntr=.3,.1

Type RM Length L Ch R = 1 ,15743.64,431.96,451.57,443.68
BEGIN DESCRIPTION:
Stations 4735.97-4880.87 developed from survey information, and the remainder developed from LiDAR
END DESCRIPTION:
XS GIS Cut Line= 6
     3193274.917    13882278.739     3193427.453    13878427.219
       3193464.8    13877624.091     3193466.859    13877341.992
     3193513.415    13877147.836 3193573.567349113876958.2488403
#Sta/Elev= 30
       0      43   19.03   42.17   40.52   38.83   54.04   39.11  160.62   41.38
  1058.7   40.48  1134.9   38.82 1320.78   40.53 1440.71   38.41 1676.81   40.12
 1736.29   38.37 1908.23      40 2022.08   38.78 2141.25   40.83 2592.52   38.77
 2647.09    40.6 2878.12   38.82 3356.93   40.45 4168.85   39.12 4559.27   41.11
 4766.57   39.75 4769.88   39.66  4783.6   32.25 4800.09   27.23 4847.63   38.68
 4880.87   39.95 5213.31   39.99 5264.04   38.67 5299.88   41.76  5339.2   42.75
#Mann= 7 ,-1 , 0
       0     .03       0   54.04     .06       0  1134.9      .1       0
 3356.93     .08       0 4766.57     .06       0 4880.87      .1       0
 5299.88     .03       0
#XS Ineff= 5 ,-1
   23.56  160.82   41.38  301.49 4559.56   41.11 4881.51 5074.33   39.96
 5107.01 5290.02   40.02    4600 4735.97   40.58
Permanent Ineff=
       F       F       F       F       F
Bank Sta=4766.57,4847.63
XS Rating Curve= 0
Exp/Cntr=.3,.1

Type RM Length L Ch R = 1 ,15292.10,256.3,271.56,269.81
BEGIN DESCRIPTION:
Stations 4905.26-5049.65 developed from survey information, and the remainder developed from LiDAR
XS 4
END DESCRIPTION:
XS GIS Cut Line= 5
 3193561.885600513882448.2520264       3193702.8      13879644.1
     3193813.569    13878423.719     3193816.677    13878413.648
 3193955.803789213877134.8565951
#Sta/Elev= 30
   11.13   43.46   41.17   42.74   71.21   38.16  116.27   40.56 1315.96   40.91
 2090.83   40.37 2173.86   38.84 2294.01   41.03 2429.18   40.59 2474.24   38.89
  2684.5   41.27 2749.46   39.07 2925.11   40.66 3060.66   38.57 3181.16   40.74
 3317.99   39.35 3407.08      41 3511.88   40.29 4625.44   40.21 4854.85   38.62
 4885.03   40.42 4934.33   39.79  4939.1   39.66  4952.8   32.25 4968.97   27.23
 5015.31   38.64 5049.65   39.95 5262.24   39.67 5290.64   41.48 5341.09   42.86
#Mann= 7 ,-1 , 0
   11.13     .03       0  116.27     .06       0 1315.96      .1       0
 3511.88     .08       0 4934.33     .06       0 5049.65      .1       0
 5290.64     .03       0
#XS Ineff= 5 ,-1
   45.66  671.66   41.47   694.5 2678.37   41.27 2685.48 3423.39   41.05
 3454.07 4905.68   40.58 5066.54 5296.38   41.03
Permanent Ineff=
       F       F       F       F       F
Bank Sta=4934.33,5015.31
XS Rating Curve= 0
Exp/Cntr=.5,.3

Type RM Length L Ch R = 1 ,15020.39,135.62,214.5,275.45
BEGIN DESCRIPTION:
US 90 HWY Access Rd Culvert XS 3
Stations 5105.35-5249.31 developed from survey information, and the remainder developed from LiDAR
END DESCRIPTION:
XS GIS Cut Line= 3
 3193842.975190313882598.2424447     3194122.375    13877913.514
 3194213.598362713877258.2418158
#Sta/Elev= 30
   82.56   42.89  134.53   34.53  164.95   35.37  262.08   40.16   363.3   40.97
  924.05   40.56  984.15   38.65 1058.35   40.91 1401.25   41.01 1539.54   39.01
 1758.74   40.92 2381.63   39.24 3178.05    40.9 3253.18   39.32  3433.5   41.27
 3745.94    39.9 4460.87    39.6 4605.58   41.38 4799.61   40.83  4855.9    38.8
 5088.87   40.76 5135.46   39.76 5139.09   39.66 5152.77   32.25 5168.81   27.23
 5212.44   38.35 5223.44   38.97 5316.04   41.43 5352.52   40.42  5437.2   43.03
#Mann= 7 ,-1 , 0
   82.56     .03       0  164.95     .06       0 1539.54      .1       0
 3745.94     .08       0 5135.46     .04       0 5223.44      .1       0
 5352.52     .03       0
#XS Ineff= 6 ,-1
    81.2  4605.4   41.38 4719.51 4799.61   40.83 4802.99 5088.84   40.76
    5130 5157.64   39.85 5182.53 5226.15   38.75 5317.41 5379.06   41.45
Permanent Ineff=
       F       F       F       F       F       F
Bank Sta=5135.46,5212.44
XS Rating Curve= 0
Exp/Cntr=.5,.3

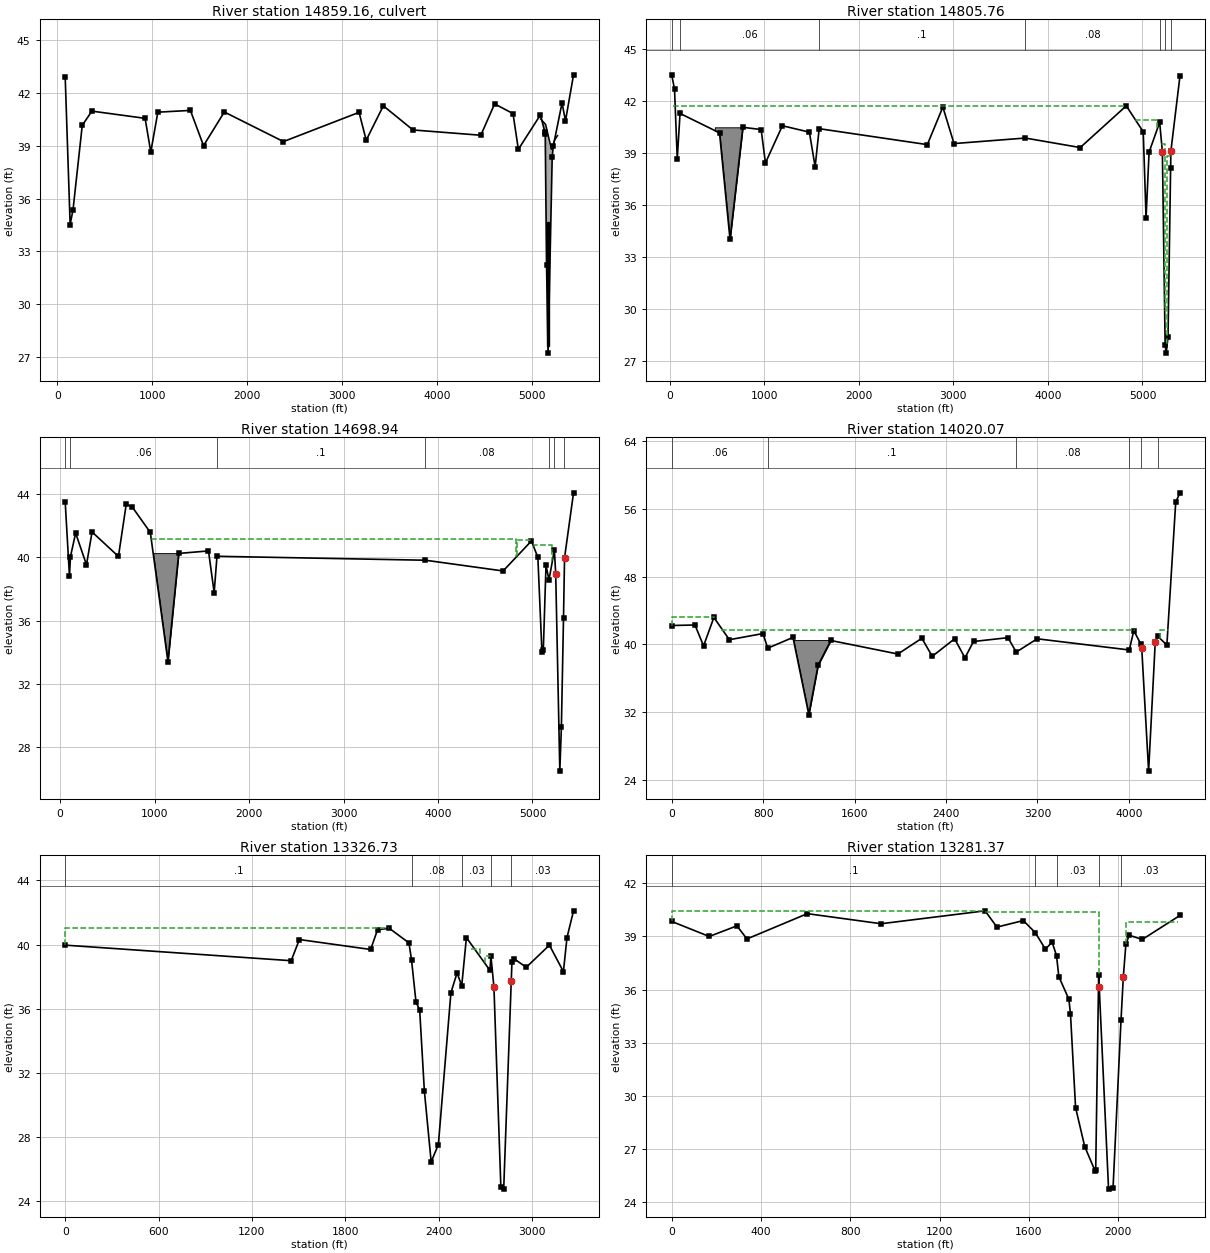
Type RM Length L Ch R = 2 ,14859.16,,,
BEGIN DESCRIPTION:
S1 US 90 HWY Access Rd
END DESCRIPTION:
Bridge Culvert--1,0,-1,-1, 0
Deck Dist Width WeirC Skew NumUp NumDn MinLoCord MaxHiCord MaxSubmerge Is_Ogee
41.51,121.67,2.5,0, 5, 5, , , .95, 0, 0,0,,
 5091.16 5142.98 5204.87 5238.92 5268.48
   40.52   40.22    38.8   39.33   39.58
                                        
 5151.82 5203.65 5265.53 5299.59 5329.16
   40.52   40.22    38.8   39.33   39.58
                                        
BR Coef=-1 , 0 , 0 ,, 0 ,,,.8,-1,,0,
WSPro=,,,, 1 ,,,, 0 ,,,, 0 ,,,,-1 ,-1 ,-1 , 0 , 0 , 0 , 0 , 0
Multiple Barrel Culv=2,7,10,121.67,.015,.2,1,9,2,27.65,27.47, 2,Culvert #1  , 0 ,41.51
  5164.2 5240.98 5175.97 5255.37
Culvert Bottom n=.015
BC Design=,, 0 ,, 0 ,,,,,,
BC HTab HWMax=43.03

Type RM Length L Ch R = 1 ,14805.76,139.32,107.13,123.08
BEGIN DESCRIPTION:
US 90 HWY Access Rd Culvert XS 2
Stations 5202.09-5317.44 developed from survey information, and the remainder developed from LiDAR
END DESCRIPTION:
XS GIS Cut Line= 3
 3194017.082854913882688.2487506     3194288.144    13877658.791
 3194459.669498913877365.9857268
#Sta/Elev= 30
   20.53    43.5   50.58   42.68   79.55   38.64     109   41.27  526.38   40.15
  637.52      34  773.44   40.47   966.9   40.34 1011.97   38.41 1191.33   40.56
 1477.01   40.19 1537.73   38.19 1580.51   40.39 2724.45   39.47 2888.57   41.64
 3006.66   39.53 3760.52   39.85 4341.37    39.3  4828.6   41.71 5007.76   40.21
  5037.8   35.24 5069.51   39.03  5181.5   40.76 5210.22   39.07 5239.44   27.92
 5250.23   27.43 5269.83   28.35 5297.42   38.14 5300.11   39.09 5396.63   43.45
#Mann= 7 ,-1 , 0
   20.53     .03       0     109     .06       0 1580.51      .1       0
 3760.52     .08       0  5181.5     .03       0 5239.44     .04       0
 5297.42     .03       0
#XS Ineff= 4 ,-1
   36.29 4826.61   41.71 4918.39 5153.31    40.9    5200 5234.35   39.48
    5262 5301.02   38.81
Permanent Ineff=
       F       F       F       F
#Block Obstruct= 1 ,-1
  477.01   772.8   40.47
Bank Sta=5210.22,5300.11
XS Rating Curve= 0
Exp/Cntr=.5,.3

Type RM Length L Ch R = 1 ,14698.94,567.11,678.89,685.58
BEGIN DESCRIPTION:
Stations 5191.88-5374.17 developed from survey information, and the remainder developed from LiDAR
XS 1
END DESCRIPTION:
XS GIS Cut Line= 3
 3194168.385744713882748.2515231     3194412.512    13877628.991
 3194564.163833113877423.2487414
#Sta/Elev= 30
    54.2    43.5   99.26   38.82  109.87   40.05   164.6   41.54  279.46   39.53
  338.39   41.61  617.77   40.06  699.94   43.36  762.96    43.2  955.23   41.58
 1141.42    33.4 1255.57   40.25 1570.93   40.41 1630.99   37.77 1660.67   40.07
 3867.69   39.82 4689.46   39.14 4989.07   41.04 5057.37      40 5100.37   34.01
 5114.95   34.12 5143.37   39.49 5175.02   38.58 5232.24   40.46 5246.29   38.94
 5289.76   26.46 5306.24   29.24 5328.69   36.15 5339.68   39.97 5434.88   44.09
#Mann= 7 ,-1 , 0
    54.2     .03       0  109.87     .06       0 1660.67      .1       0
 3867.69     .08       0 5175.02     .03       0 5232.24     .04       0
 5328.69     .03       0
#XS Ineff= 4 ,-1
   36.29  701.61   43.32  958.62 4829.58   41.14 4834.83 4970.48    41.1
  5015.7 5211.64   40.78
Permanent Ineff=
       F       F       F       F
#Block Obstruct= 1 ,-1
  980.77 1255.93   40.27
Bank Sta=5246.29,5339.68
XS Rating Curve= 0
Exp/Cntr=.3,.1

Type RM Length L Ch R = 1 ,14020.07,840.36,693.22,573.96
BEGIN DESCRIPTION:
Stations 4071.23-4256.36 developed from survey information, and the remainder developed from LiDAR
END DESCRIPTION:
XS GIS Cut Line= 4
     3194502.911    13882006.441     3194786.041    13878217.696
     3195138.225    13877806.354 3195177.626598513877708.2473323
#Sta/Elev= 30
       0   42.22  203.76   42.28  278.97   39.81  369.22   43.17   504.6   40.54
   798.9   41.27   840.1   39.54 1061.14   40.81 1199.65   31.69 1280.93   37.53
 1392.07   40.45  1978.7   38.85 2188.38   40.71 2279.53   38.58 2475.08   40.65
 2565.33    38.4 2640.54   40.33 2941.37   40.78 3014.48   39.08 3197.08   40.65
 4002.84   39.33 4042.29   41.61 4101.67   40.09 4111.56   39.62 4171.98   25.01
 4230.16   40.29 4249.93   40.97 4331.75   39.91 4409.31   56.82 4446.55    57.9
#Mann= 6 ,-1 , 0
       0     .06       0   840.1      .1       0 3014.48     .08       0
 4002.84     .03       0 4101.67     .04       0 4249.93     .03       0
#XS Ineff= 3 ,-1
   -1.87   371.5   43.18  433.47 4042.34   41.66 4272.89 4350.86   41.73
Permanent Ineff=
       F       F       F
#Block Obstruct= 1 ,-1
  1065.9 1409.01    40.5
Bank Sta=4111.56,4230.16
XS Rating Curve= 0
Exp/Cntr=.3,.1

Type RM Length L Ch R = 1 ,13326.73,101.8,45.47,13.47
BEGIN DESCRIPTION:
Stations 2732.66-2883.15 developed from survey information, and the remainder developed from LiDAR
XS 4
END DESCRIPTION:
XS GIS Cut Line= 6
     3195349.172    13881168.834     3195489.362    13878507.876
     3195510.606    13878467.455     3195591.071    13878297.745
     3195595.981    13878129.685     3195602.667    13877928.239
#Sta/Elev= 30
       0   39.96  1452.6   38.99 1505.38   40.31 1963.31   39.69 2008.37   40.93
 2083.47   41.01 2209.89    40.1 2226.55   39.02 2255.09   36.41 2278.74   35.92
 2308.78   30.88  2352.6   26.45 2398.91   27.53 2479.45   36.99 2519.08   38.23
 2549.12   37.43 2579.16   40.43 2730.35   38.39 2736.78   39.28 2756.18   37.33
 2800.62   24.88 2818.83   24.75 2867.58   37.75 2871.88    38.9 2887.26    39.1
 2963.86   38.58 3112.73   39.96 3202.78   38.31 3225.71   40.43 3267.82    42.1
#Mann= 5 ,-1 , 0
       0      .1       0 2226.55     .08       0 2549.12     .03       0
 2736.78     .04       0 2867.58     .03       0
#XS Ineff= 6 ,-1
       0 2083.47   41.01 2109.15 2579.16   40.43 2610.94 2664.65   39.75
 2696.68 2736.78   39.28 2887.26 3027.87    39.1 3112.73    3250   39.96
Permanent Ineff=
       F       F       F       F       F       F
Bank Sta=2756.18,2867.58
XS Rating Curve= 0
Exp/Cntr=.5,.3

Type RM Length L Ch R = 1 ,13281.37,129.35,125.83,127.28
BEGIN DESCRIPTION:
Sheldon Rd Bridge XS 3
Stations 1912.27-2019.97 developed from survey information, and the remainder developed from LiDAR
END DESCRIPTION:
XS GIS Cut Line= 3
     3195499.789    13880355.008     3195608.236    13878135.246
 3195611.270450313878081.1707029
#Sta/Elev= 30
       0   39.85  168.16      39  292.11    39.6  337.16   38.86  607.48   40.29
  937.88   39.72 1403.43   40.45 1456.81   39.53 1574.86    39.9 1628.87   39.21
 1673.76   38.28 1703.79   38.68 1723.52   37.92 1733.83   36.73 1778.88   35.45
 1786.13   34.61 1808.92   29.32 1849.83   27.12  1897.2   25.71 1899.02   25.77
 1912.27   36.83  1914.7   36.16 1956.68   24.71  1976.7   24.78 2012.54    34.3
 2022.75   36.72 2034.19   38.56  2049.2   39.07 2107.41   38.83 2276.57   40.19
#Mann= 5 ,-1 , 0
       0      .1       0 1628.87     .08       0 1723.52     .03       0
  1914.7    .035       0 2012.54     .03       0
#XS Ineff= 3 ,-1
       0 1399.54   40.45 1403.03 1912.27   40.37 2034.13 2269.25    39.8
Permanent Ineff=
       F       F       F
Bank Sta=1914.7,2022.75
XS Rating Curve= 0
Exp/Cntr=.5,.3

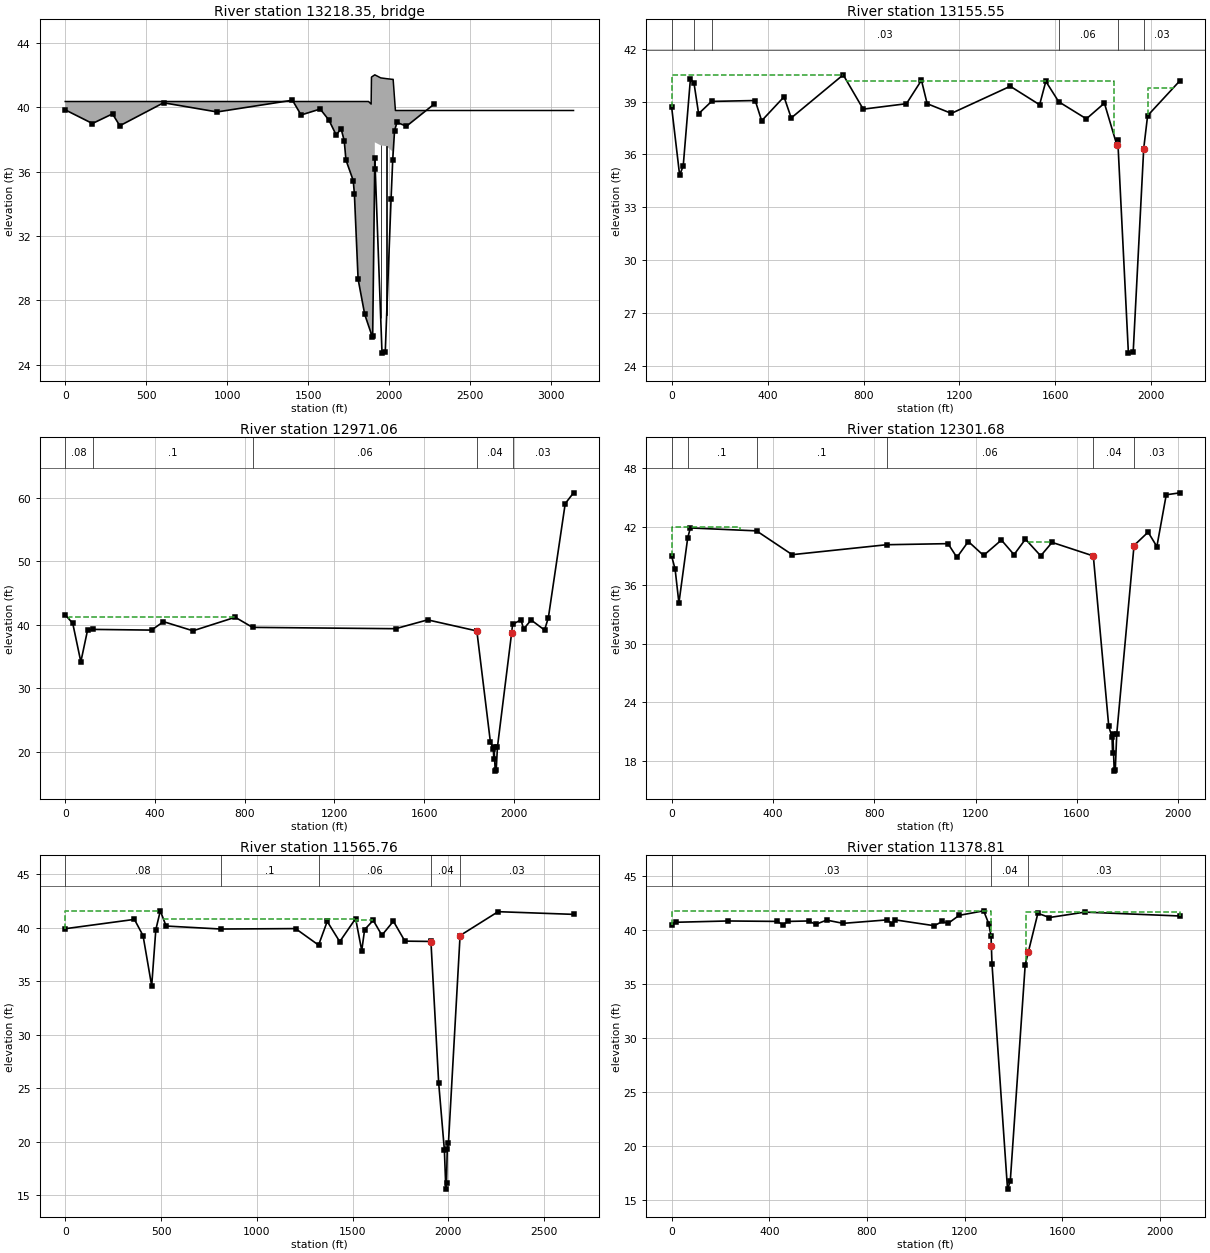
Type RM Length L Ch R = 3 ,13218.35,,,
BEGIN DESCRIPTION:
S2 Sheldon Road
END DESCRIPTION:
Bridge Culvert--1,0,-1,-1, 0
Deck Dist Width WeirC Skew NumUp NumDn MinLoCord MaxHiCord MaxSubmerge Is_Ogee
13.42,94.6,2.6,0, 15, 12, , , .95, 0, 0,0,,
       0    1400 1873.54 1889.46  1891.6 1912.07 1912.27 1948.64 1985.27 2019.97
 2021.62 2025.45 2039.47 2048.95 3139.57
   40.37   40.37   40.37   40.21   41.89   42.03   42.03   41.84   41.79   41.75
   41.75   41.75   39.81   39.81   39.81
                                                   37.83   37.64   37.59   37.27
                                        
       0 1820.56 1836.48 1857.17 1860.22 1896.59 1933.22 1966.57 1967.91 1986.48
 1995.96  3101.8
   40.37   40.37   40.21   40.11   40.11   40.02   39.92   39.84   39.84   39.81
   39.81   39.81
                                   37.83   37.64   37.59   37.27   37.27
                
Pier Skew, UpSta & Num, DnSta & Num=  ,1948.64, 4 ,1896.59, 4 , 3 , 3 , 0 ,,
    1.35    1.35     2.6     2.6
      24   35.04   35.04   37.64
    1.35    1.35     2.6     2.6
      24   35.04   35.04   37.64
Pier Skew, UpSta & Num, DnSta & Num=  ,1985.27, 4 ,1933.22, 4 , 3 , 3 , 0 ,,
    1.35    1.35     2.6     2.6
      24   34.99   34.99   37.59
    1.35    1.35     2.6     2.6
      24   34.99   34.99   37.59
BR Coef=-1 , 1 , 1 ,1.25, 0 ,,,.8,0,2,0,
WSPro=,,,, 1 ,,,, 0 ,,,, 0 ,,,,-1 ,-1 ,-1 , 0 , 0 , 0 , 0 , 0
BC Design=,, 0 ,, 0 ,,,,,,
BC HTab HWMax=40.45

Type RM Length L Ch R = 1 ,13155.55,109.52,184.39,259.34
BEGIN DESCRIPTION:
Sheldon Rd Bridge XS 2
Stations 1860.22-1967.91 developed from survey information, and the remainder developed from LiDAR
END DESCRIPTION:
XS GIS Cut Line= 2
     3195645.622    13880306.397 3195729.558671613878188.2542308
#Sta/Elev= 30
       0   38.67   33.18   34.82   48.19   35.35   78.21   40.29   93.22   40.04
  112.36   38.31   166.3   39.01  348.42   39.06   375.3   37.91  468.52   39.27
  498.54   38.07   715.3   40.52  798.78   38.57  979.12   38.88 1041.64   40.21
 1065.37   38.88 1166.45   38.33 1411.92   39.87 1534.35   38.82 1560.27   40.15
 1614.07   38.99 1729.41   38.02 1804.56   38.91 1856.33   36.54 1860.22   36.83
 1904.62   24.71 1924.66   24.78 1968.48   36.33 1984.71    38.2 2119.81   40.19
#Mann= 6 ,-1 , 0
       0     .08       0   93.22      .1       0   166.3     .03       0
 1614.07     .06       0 1860.22     .04       0 1968.48     .03       0
#XS Ineff= 3 ,-1
       0   715.3   40.52  727.97 1842.64   40.15 1985.45    2095    39.8
Permanent Ineff=
       F       F       F
Bank Sta=1856.33,1968.48
XS Rating Curve= 0
Exp/Cntr=.5,.3

Type RM Length L Ch R = 1 ,12971.06,642.38,668.81,654.25
BEGIN DESCRIPTION:
Stations 1807.63-2032.31 developed from survey information, and the remainder developed from LiDAR
XS 1
END DESCRIPTION:
XS GIS Cut Line= 4
     3195748.921    13880342.855     3195821.476    13878621.163
     3195949.922    13878297.557     3195991.428    13878107.013
#Sta/Elev= 30
       0   41.55    33.5   40.23   69.67   34.16    99.7   39.15   124.7   39.26
  384.95   39.15  438.18   40.48  569.69   39.04  758.06   41.17  835.35   39.58
 1472.65   39.37 1616.04   40.76 1834.94   39.02 1835.29   39.01 1895.75   21.54
 1908.71   20.44 1911.21   18.84 1911.92   20.78 1917.26   16.96 1921.52    17.1
 1927.16   20.76 1990.28   38.67 1994.85   40.07 2032.31   40.76 2043.75   39.32
 2077.33   40.74  2137.2   39.16 2154.23   41.12 2229.31   59.05  2266.4   60.75
#Mann= 5 ,-1 , 0
       0     .08       0   124.7      .1       0  835.35     .06       0
 1835.29     .04       0 1994.85     .03       0
#XS Ineff= 3 ,-1
   16.86  758.06   41.17 2032.31    2160   40.76     765 1616.04   40.76
Permanent Ineff=
       F       F       F
Bank Sta=1834.94,1990.28
XS Rating Curve= 0
Exp/Cntr=.3,.1

Type RM Length L Ch R = 1 ,12301.68,755.15,736.01,458.6
BEGIN DESCRIPTION:
Stations 1955.93-2180.61 developed from survey information, and the remainder developed from LiDAR
END DESCRIPTION:
XS GIS Cut Line= 3
     3196339.884    13880346.741     3196443.865    13878823.668
     3196622.497    13878377.818
#Sta/Elev= 30
       0   38.99   13.53   37.67   28.56    34.2   63.24   40.86   73.67   41.89
  335.02   41.59   475.8   39.15  848.98   40.17 1091.03   40.28 1126.11   38.87
 1171.21    40.5 1231.35   39.07 1301.84   40.65 1351.63   39.15 1396.74   40.74
 1456.88   39.03 1501.98   40.41 1664.68   39.02 1725.71   21.54 1738.67   20.44
 1741.16   18.84 1741.88   20.78 1747.21   16.96 1751.48    17.1 1757.11   20.76
 1825.42   40.09 1880.99   41.46  1915.6   39.98  1952.6   45.29 2006.92   45.49
#Mann= 6 ,-1 , 0
       0     .08       0   63.24      .1       0  335.02      .1       0
  848.98     .06       0 1664.68     .04       0 1825.42     .03       0
#XS Ineff= 3 ,-1
       0  269.12   41.94     300 1396.74   40.74    1410 1501.98   40.41
Permanent Ineff=
       F       F       F
Bank Sta=1664.68,1825.42
XS Rating Curve= 0
Exp/Cntr=.3,.1

Type RM Length L Ch R = 1 ,11565.76,551.57,187.02,13.48
BEGIN DESCRIPTION:
Stations 1987.59-2145.85 developed from survey information, and the remainder developed from LiDAR
XS 4
END DESCRIPTION:
XS GIS Cut Line= 5
     3197079.811    13880814.064     3197169.526    13878956.575
     3197257.685    13878767.757     3197106.414    13878701.949
     3196708.052     13878568.98
#Sta/Elev= 30
       0    39.9  361.24   40.77  406.29   39.25  451.34   34.56  472.93   39.81
   496.4   41.57  526.43   40.15  811.76   39.87 1202.22   39.91 1322.36   38.37
 1367.41   40.58 1432.75   38.69 1515.69   40.85 1547.62   37.85 1562.64   39.82
 1607.69   40.68 1652.74   39.29 1712.81    40.6 1772.88   38.74 1908.71   38.71
 1908.73    38.7 1949.05   25.52 1978.98   19.22 1986.52   15.58    1990   16.18
 1993.92   19.32  2000.1   19.88 2060.83   39.26 2259.27   41.49 2652.97   41.24
#Mann= 5 ,-1 , 0
       0     .08       0  811.76      .1       0 1322.36     .06       0
 1908.71     .04       0 2060.83     .03       0
#XS Ineff= 3 ,-1
       0   496.4   41.57     510 1517.58   40.85    1520 1607.69   40.68
Permanent Ineff=
       F       F       F
Bank Sta=1908.73,2060.83
XS Rating Curve= 0
Exp/Cntr=.5,.3

Type RM Length L Ch R = 1 ,11378.81,201.82,202.57,266.46
BEGIN DESCRIPTION:
US 90 HWY Bridge XS 3
Stations 2284.84-2472.88 developed from survey information, and the remainder developed from LiDAR
END DESCRIPTION:
XS GIS Cut Line= 5
     3198620.246    13879399.114     3197509.232    13878868.376
     3197258.712    13878750.302     3197100.479    13878686.689
     3196716.418    13878560.364
#Sta/Elev= 30
       0   40.52   16.44   40.76  230.18   40.88  432.68   40.84  455.18   40.54
  477.82   40.84  560.83   40.88  590.17   40.57  635.17   40.96  702.67   40.66
  882.66   40.98  902.72   40.63  916.41   40.98 1076.17   40.44 1109.41   40.84
 1132.26   40.65 1178.04    41.4 1278.49   41.82 1299.02   40.64  1308.7    39.5
 1310.17   38.52 1312.59   36.91 1376.28   16.04 1387.58   16.79 1448.77   36.83
 1461.23   37.98 1500.63   41.59 1547.87    41.2 1692.79    41.7 2083.07   41.34
#Mann= 3 ,-1 , 0
       0     .03       0 1310.17     .04       0 1461.23     .03       0
#XS Ineff= 4 ,-1
                                                 1452.96 2083.07    41.7
       0 1308.65   41.82
Permanent Ineff=
       F       F       F       F
Bank Sta=1310.17,1461.23
XS Rating Curve= 0
Exp/Cntr=.5,.3

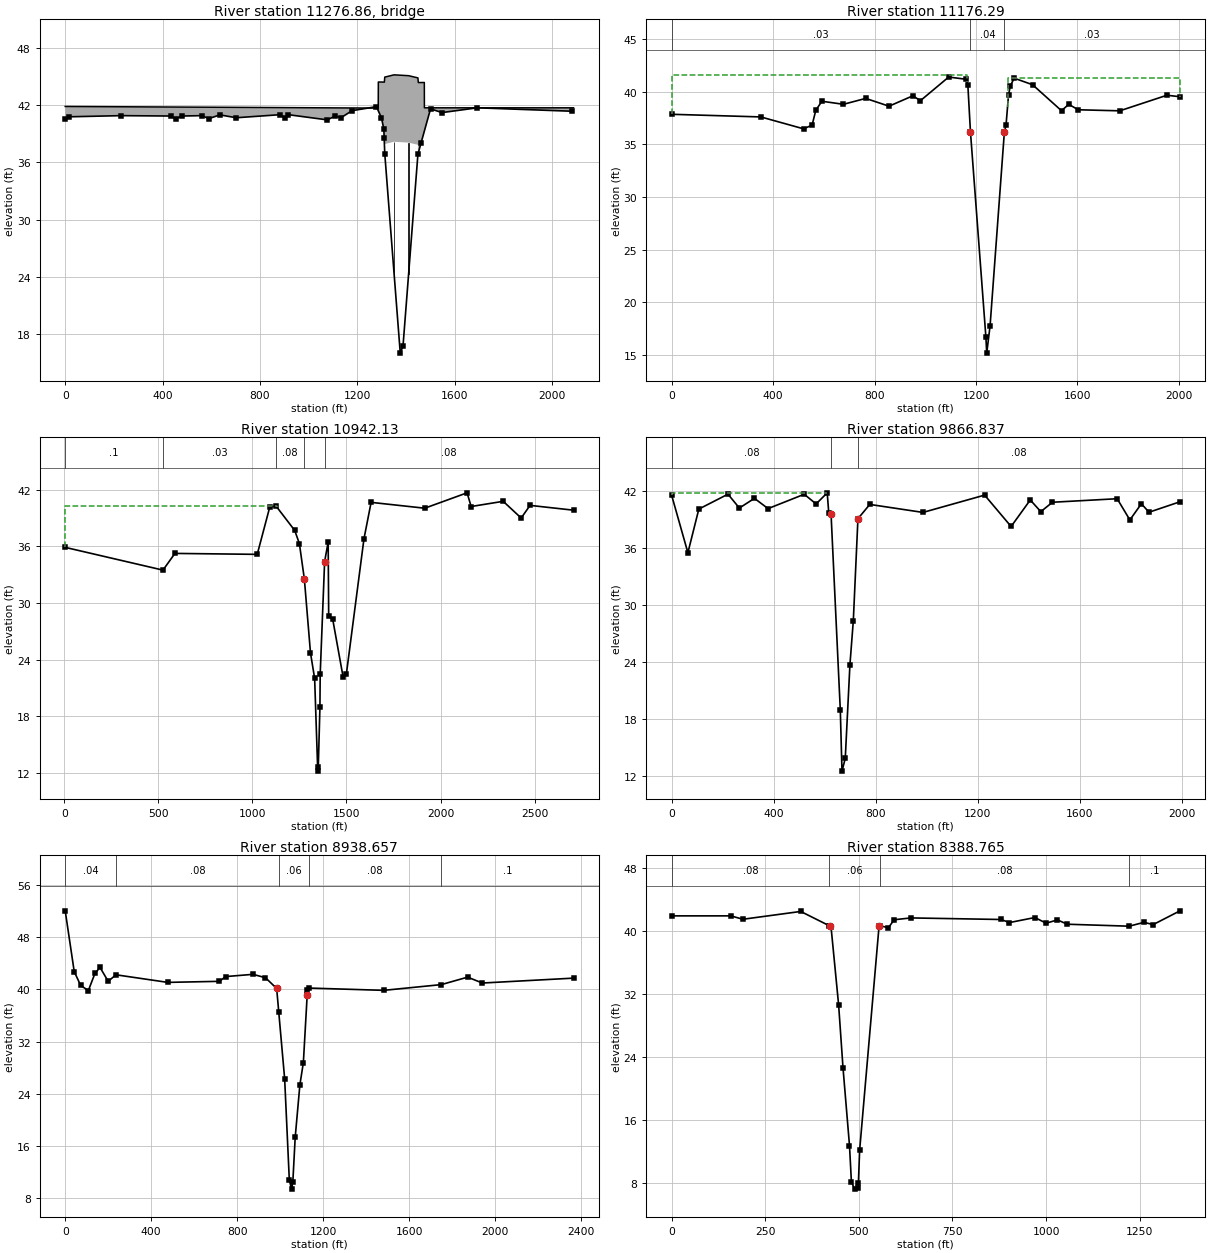
Type RM Length L Ch R = 3 ,11276.86,,,
BEGIN DESCRIPTION:
S3 & S4 US 90 HWY (North & Southbound)
END DESCRIPTION:
Bridge Culvert--1,0,-1,-1, 0
Deck Dist Width WeirC Skew NumUp NumDn MinLoCord MaxHiCord MaxSubmerge Is_Ogee
3.94,187,2.6,0, 12, 12, , , .95, 0, 0,0,,
       0 1285.74 1286.21 1310.96 1312.59  1350.7 1410.66 1448.77 1450.52 1475.12
 1475.43    2088
   41.84   41.67    44.4   44.39   44.91   45.15   45.06   44.83   44.34   44.35
    41.7    41.7
                                   37.91   38.15   38.06   37.83
                
       0 1163.08 1163.11 1175.05 1176.58 1214.99  1274.9 1313.36 1314.84 1326.87
 1327.13    4133
    41.6   41.62   44.18   44.15   44.74   44.76   44.74   44.59   43.94      44
   41.35   41.33
                                   37.74   37.76   37.74   37.59
                
Pier Skew, UpSta & Num, DnSta & Num=  ,1350.7, 4 ,1214.99, 4 , 3 , 3 , 0 ,,
    1.35    1.35       3       3
      15 35.1546 35.1546 38.1546
    1.35    1.35       3       3
      15 34.7633 34.7633 37.7633
Pier Skew, UpSta & Num, DnSta & Num=  ,1410.66, 4 ,1274.9, 4 , 3 , 3 , 0 ,,
    1.35    1.35       3       3
      15   35.06   35.06   38.06
    1.35    1.35       3       3
      15   34.74   34.74   37.74
BR Coef=-1 , 1 , 1 ,1.25, 0 ,,,.8,0,2,0,
WSPro=,,,, 1 ,,,, 0 ,,,, 0 ,,,,-1 ,-1 ,-1 , 0 , 0 , 0 , 0 , 0
BC Design=,, 0 ,, 0 ,,,,,,
BC HTab HWMax=42.75

Type RM Length L Ch R = 1 ,11176.29,22.39,234.32,421.87
BEGIN DESCRIPTION:
US 90 HWY Bridge XS 2
Stations 1645.51-1782.29 developed from survey information, and the remainder developed from LiDAR
END DESCRIPTION:
XS GIS Cut Line= 4
     3198581.302    13879165.453     3197547.221    13878667.138
     3197341.877    13878565.492     3196802.879    13878243.789
#Sta/Elev= 30
       0   37.85  351.56    37.6   520.1   36.47  553.81   36.82  568.47   38.24
  592.48   39.09   677.4    38.8  765.25   39.36  857.18   38.62  951.44   39.61
  980.78   39.14 1092.48   41.39 1160.51   41.18    1168   40.65 1178.29   36.19
 1239.23   16.68 1242.47   15.16 1255.75   17.77 1311.98   36.14 1318.64   36.83
 1328.45   39.67 1335.37   40.54 1350.84   41.28 1423.29   40.66  1537.4   38.19
 1566.05    38.8 1603.04   38.28 1767.13   38.18  1953.1   39.66 2004.71   39.52
#Mann= 3 ,-1 , 0
       0     .03       0 1178.29     .04       0 1311.98     .03       0
#XS Ineff= 2 ,-1
       0 1164.68    41.6  1324.7 2004.71   41.29
Permanent Ineff=
       F       F
Bank Sta=1178.29,1311.98
XS Rating Curve= 0
Exp/Cntr=.5,.3

Type RM Length L Ch R = 1 ,10942.13,871.63,1075.47,1204.44
BEGIN DESCRIPTION:
Stations 1640.03-1869.91 developed from survey information, and the remainder developed from LiDAR
XS 1
END DESCRIPTION:
XS GIS Cut Line= 4
 3198581.368297813879146.0679793     3197547.386    13878642.019
     3197624.738     13878314.97     3196664.413    13877568.767
#Sta/Elev= 30
    4.74   35.89  524.47   33.48   588.1   35.25 1025.63   35.15 1091.84   40.13
 1125.22   40.28 1225.08   37.68 1249.87   36.28 1276.29   32.52 1308.77   24.71
 1330.86      22  1347.4   12.18 1350.14   12.58 1359.02   18.98 1360.34   22.43
  1383.9   34.38 1402.77   36.47 1405.54   28.58 1426.87   28.28  1482.6   22.11
 1499.85   22.51 1593.11    36.8 1631.11   40.66 1916.05   40.04 2141.24   41.67
    2163   40.22 2333.26   40.77 2428.94      39 2476.04   40.34 2707.27   39.83
#Mann= 5 ,-1 , 0
    4.74      .1       0  524.47     .03       0 1125.22     .08       0
 1276.29     .06       0  1383.9     .08       0
#XS Ineff= 2 ,-1
    4.74 1129.41    40.3 1402.77 1757.68   36.47
Permanent Ineff=
       F       F
Bank Sta=1276.29,1383.9
XS Rating Curve= 0
Exp/Cntr=.3,.1

Type RM Length L Ch R = 1 ,9866.837,931.12,928.59,891.27
BEGIN DESCRIPTION:
Stations 804.68-965.65 developed from survey information, and the remainder developed from LiDAR
END DESCRIPTION:
XS GIS Cut Line= 3
     3198611.591    13879217.378     3198637.173    13878715.418
     3198717.227    13877226.994
#Sta/Elev= 30
       0    41.5   63.58   35.47  106.45   40.06  220.78   41.63  265.38   40.17
  324.55   41.19  377.98   40.11  519.81   41.62  566.28    40.6  609.94   41.77
   615.9   39.65  624.98   39.52  661.23   18.92  667.81   12.51  680.65   13.85
  698.91   23.68  712.22   28.32  730.36   39.05  776.87   40.55  985.48   39.71
 1227.05   41.53 1330.98   38.23 1406.09   41.02 1447.42   39.79 1493.12   40.78
 1746.78   41.15 1796.65   38.92 1841.72   40.62 1871.76   39.73 1993.19   40.83
#Mann= 3 ,-1 , 0
       0     .08       0  624.98     .06       0  730.36     .08       0
#XS Ineff= 1 ,-1
       0  609.94   41.77
Permanent Ineff=
       F
Bank Sta=624.98,730.36
XS Rating Curve= 0
Exp/Cntr=.3,.1

Type RM Length L Ch R = 1 ,8938.657,542.36,549.62,519.04
BEGIN DESCRIPTION:
Stations 956.21-1175.07 developed from survey information, and the remainder developed from LiDAR
END DESCRIPTION:
XS GIS Cut Line= 2
     3199580.942    13879640.188     3199526.835    13877275.412
#Sta/Elev= 30
       0      52   41.95    42.7   71.96   40.58  107.68    39.8  138.39   42.42
  161.98   43.34  199.81   41.22  236.54   42.21  477.07   41.05  717.13   41.21
  747.14   41.94  873.93   42.28  931.97   41.76     984   40.12  993.47   36.59
 1021.18   26.28 1042.87    10.8 1053.48    9.41  1059.2   10.51 1070.18   17.32
 1091.94   25.35 1108.19   28.77 1125.93   39.07  1127.4   39.92 1135.39   40.18
 1482.33   39.83 1750.39   40.71 1872.43   41.85 1941.28   40.95  2365.4    41.7
#Mann= 5 ,-1 , 0
       0     .04       0  236.54     .08       0  993.47     .06       0
 1135.39     .08       0 1750.39      .1       0
Bank Sta=984,1125.93
XS Rating Curve= 0
Exp/Cntr=.3,.1

Type RM Length L Ch R = 1 ,8388.765,138.42,139.83,138.38
BEGIN DESCRIPTION:
Stations 372.69-567.74 developed from survey information, and the remainder developed from LiDAR
XS 4
END DESCRIPTION:
XS GIS Cut Line= 2
     3200120.478    13879110.816     3200024.123     13877756.65
#Sta/Elev= 30
       0   41.92     158   41.92  190.27   41.49  344.66   42.48  420.85   40.67
  423.57   40.59   425.6   40.53  445.87   30.63  457.57   22.65  474.91   12.78
  479.98    8.19  488.43    7.25  496.59    7.45  498.68       8  501.98   12.18
   553.9   40.64  556.61   40.66  579.03   40.42  594.07   41.43  639.18   41.66
  879.79   41.46   902.1   41.07  970.02   41.71 1000.09   40.99 1030.17   41.41
 1056.53   40.86 1221.83   40.61 1261.62    41.1 1285.81   40.81 1357.59   42.56
#Mann= 4 ,-1 , 0
       0     .08       0  420.85     .06       0  556.61     .08       0
 1221.83      .1       0
Bank Sta=423.57,553.9
XS Rating Curve= 0
Exp/Cntr=.5,.3