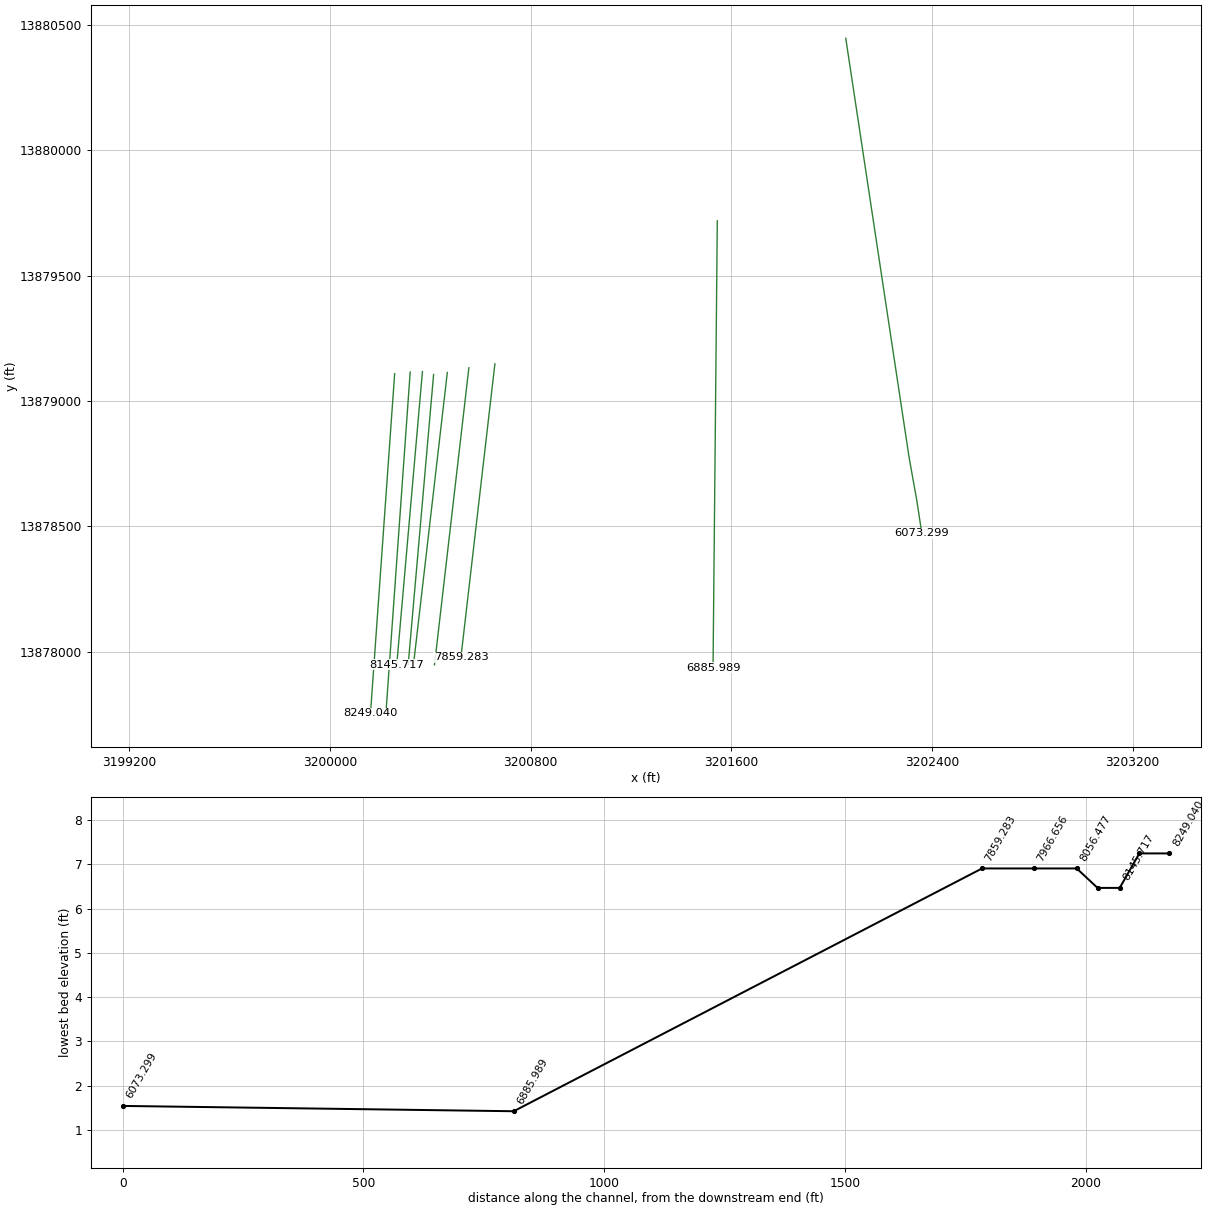
HEC-RAS study G103-07-00.prj: G103-07-00

--- G103-07-00.g01 (geometry) --- (continued)

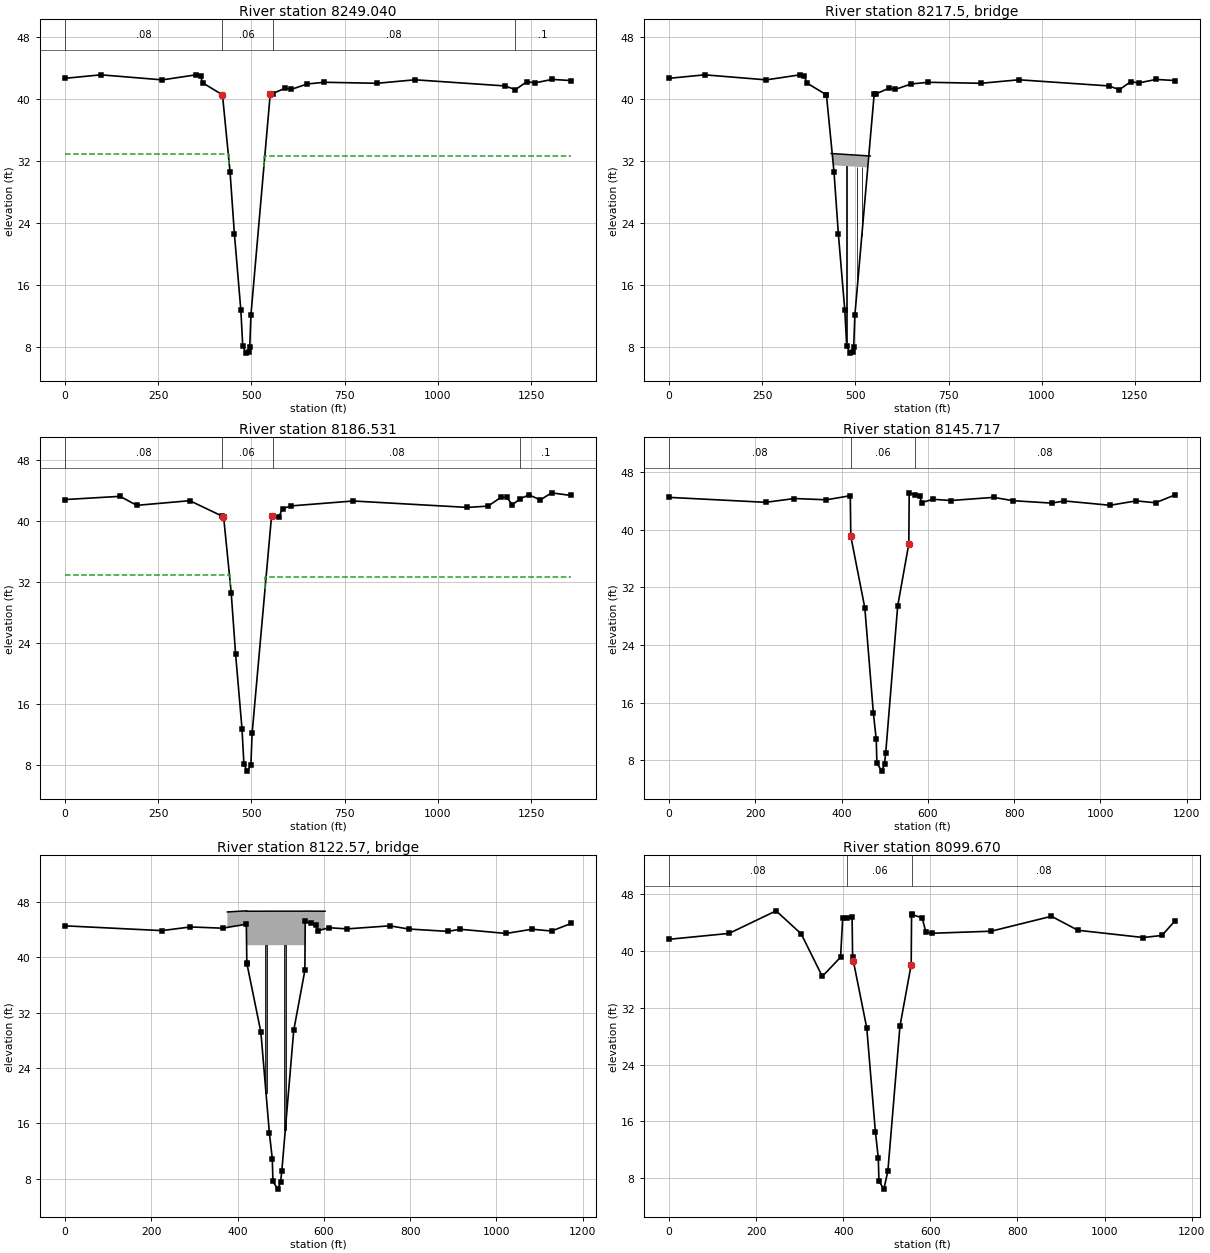
Type RM Length L Ch R = 1 ,8249.040,61.85,62.53,61.83
BEGIN DESCRIPTION:
1.5 Kinder Morgan Pipe Bridge XS 3
Stations 369.35-564.40 developed from survey information, and the remainder developed from LiDAR
END DESCRIPTION:
XS GIS Cut Line= 2
     3200257.834    13879108.601      3200161.48    13877754.434
#Sta/Elev= 30
       0   42.66    95.6   43.11  261.01   42.46  351.24   43.11  363.42   42.92
  369.35   42.07  420.85   40.57  422.25   40.53  442.53   30.63  454.22   22.65
  471.57   12.78  476.64    8.19  485.08    7.25  493.24    7.45  495.34       8
  498.64   12.18  550.41   40.64  556.61   40.69     591    41.4  607.42   41.24
  649.53   41.93  695.21   42.15  836.96   42.02  938.68   42.47 1180.07   41.68
 1208.26    41.2 1238.48   42.21 1261.48   42.08 1306.87   42.52 1357.59   42.37
#Mann= 4 ,-1 , 0
       0     .08       0  420.85     .06       0  556.61     .08       0
 1208.26      .1       0
#XS Ineff= 2 , 0
       0  440.62    32.9  533.38       0   32.63
Permanent Ineff=
       F       F
Bank Sta=422.25,550.41
XS Rating Curve= 0
Exp/Cntr=.5,.3

Type RM Length L Ch R = 3 ,8217.5  ,,,
BEGIN DESCRIPTION:
S5 Pipe 1.5 Kinder Morgan
(three pipes, the largest one was modeled: Pipe 8 and Pipe 4 were not modeled)
END DESCRIPTION:
Bridge Culvert--1,0,-1,-1, 0
Deck Dist Width WeirC Skew NumUp NumDn MinLoCord MaxHiCord MaxSubmerge Is_Ogee
9.95,1.5,2.6,0, 4, 4, , , .95, 0, 0,0,,
     435  438.66  530.65     540
   32.97   32.96   32.68   32.65
   31.47   31.46   31.18   31.15
     435  438.66  530.65     540
   32.97   32.96   32.68   32.65
   31.47   31.46   31.18   31.15
Pier Skew, UpSta & Num, DnSta & Num=  ,476.13, 2 ,476.13, 2 , 0 , 0 , 0 ,,
    1.35    1.35
   10.67      32
    1.35    1.35
   10.67      32
Pier Skew, UpSta & Num, DnSta & Num=  ,504.37, 2 ,504.37, 2 , 0 , 0 , 0 ,,
    1.35    1.35
   15.13      32
    1.35    1.35
   15.13      32
Pier Skew, UpSta & Num, DnSta & Num=  ,517.16, 2 ,517.16, 2 , 0 , 0 , 0 ,,
    1.35    1.35
    25.8      32
    1.35    1.35
    25.8      32
BR Coef=-1 , 1 , 1 ,1.25, 0 ,,,.8,0,2,0,
WSPro=,,,, 1 ,,,, 0 ,,,, 0 ,,,,-1 ,-1 ,-1 , 0 , 0 , 0 , 0 , 0
BC Design=,, 0 ,, 0 ,,,,,,
BC HTab HWMax=43.11

Type RM Length L Ch R = 1 ,8186.531,45.25,40.87,36.8
BEGIN DESCRIPTION:
1.5 Kinder Morgan Pipe Bridge XS 2
Stations 372.48-567.53 developed from survey information, and the remainder developed from LiDAR
END DESCRIPTION:
XS GIS Cut Line= 2
     3200319.748    13879115.161     3200223.394    13877760.995
#Sta/Elev= 30
       0   42.82  147.29   43.24   192.4   42.06  334.57   42.67  420.85   40.66
  423.57   40.58  425.38   40.53  445.66   30.63  457.35   22.65   474.7   12.78
  479.77    8.19  488.21    7.25  498.47       8  501.77   12.18   553.9   40.65
  556.61   40.67  573.23   40.49  583.39   41.64  607.18   41.99  773.18   42.63
 1079.64   41.79 1134.74   41.96 1169.86   43.12  1184.9   43.12 1199.94   42.13
 1221.83   42.95 1245.05   43.43 1275.13   42.77 1305.21    43.7 1357.59   43.35
#Mann= 4 ,-1 , 0
       0     .08       0  420.85     .06       0  556.61     .08       0
 1221.83      .1       0
#XS Ineff= 2 , 0
       0   443.7    32.9  536.45       0   32.63
Permanent Ineff=
       F       F
Bank Sta=423.57,553.9
XS Rating Curve= 0
Exp/Cntr=.5,.3

Type RM Length L Ch R = 1 ,8145.717,45.93,46.03,45.91
BEGIN DESCRIPTION:
Railroad Bridge XS 3
Stations 398.68-581.10 developed from survey information, and the remainder developed from LiDAR
END DESCRIPTION:
XS GIS Cut Line= 2
      3200368.52    13879116.839 3200266.161626413877948.2400213
#Sta/Elev= 30
       0   44.53  224.45   43.84  290.74   44.37  364.95   44.19  420.19   44.76
  421.38   39.12  421.61   39.05  453.88   29.17  473.73   14.52  480.36   10.88
  481.86    7.59  493.17    6.47  499.52    7.47  502.36    9.03  530.07   29.42
  555.89   38.08  556.75   45.16  571.21   44.88   581.1   44.68  585.83   43.81
  611.87   44.26   653.4   44.09  752.82   44.53  796.63   44.07  886.98   43.73
  916.45   44.03 1022.49   43.43 1082.72   44.04 1127.89   43.78 1173.07   44.87
#Mann= 3 ,-1 , 0
       0     .08       0  421.61     .06       0  571.21     .08       0
Bank Sta=421.38,555.89
XS Rating Curve= 0
Exp/Cntr=.5,.3

Type RM Length L Ch R = 3 ,8122.57 ,,,
BEGIN DESCRIPTION:
S6 Railroad Bridge
END DESCRIPTION:
Bridge Culvert--1,0,-1,-1, 0
Deck Dist Width WeirC Skew NumUp NumDn MinLoCord MaxHiCord MaxSubmerge Is_Ogee
12,19,2.6,0, 7, 9, , , .95, 0, 0,0,,
  376.24  420.58  420.85  489.04  556.04  556.41  602.64
   46.54    46.7   46.64   46.65   46.65   46.66   46.64
                   41.72   41.73   41.73
     200  376.24  413.25  420.85  489.04  556.04  556.04  602.64     900
      45   46.54   46.75   46.64   46.65   46.65   46.71   46.64    44.5
                           41.72   41.73   41.73
Pier Skew, UpSta & Num, DnSta & Num=  ,465.9, 4 ,465.9, 4 , 3 , 3 , 0 ,,
     2.5     2.5     4.6     4.6
   24.86   40.43   40.43   41.73
     2.5     2.5     4.6     4.6
   24.86   40.43   40.43   41.73
Pier Skew, UpSta & Num, DnSta & Num=  ,510.47, 4 ,510.47, 4 , 3 , 3 , 0 ,,
     2.5     2.5     4.6     4.6
   14.76   40.43   40.43   41.73
     2.5     2.5     4.6     4.6
   14.76   40.43   40.43   41.73
BR Coef=-1 , 1 , 1 ,1.25, 0 ,,,.8,0,2,0,
WSPro=,,,, 1 ,,,, 0 ,,,, 0 ,,,,-1 ,-1 ,-1 , 0 , 0 , 0 , 0 , 0
BC Design=,, 0 ,, 0 ,,,,,,
BC HTab HWMax=45.16

Type RM Length L Ch R = 1 ,8099.670,48.26,43.25,33.74
BEGIN DESCRIPTION:
Railroad Bridge XS 2
Stations 398.76-581.18 developed from survey information, and the remainder developed from LiDAR
END DESCRIPTION:
XS GIS Cut Line= 2
     3200413.114    13879105.563 3200311.742498413877948.2397803
#Sta/Elev= 30
       0   41.66  137.84   42.49  245.78   45.67  303.47   42.42  351.88   36.43
  393.82   39.14  398.76   44.69  408.01   44.72  420.27   44.76  421.46   39.12
  422.97   38.66  453.96   29.17  473.81   14.52  480.44   10.88  481.94    7.59
  493.25    6.47  502.44    9.03  530.16   29.42  555.97   38.08  556.83   45.16
  557.61   45.15  581.18   44.68  589.56    42.7  604.62   42.51  739.53    42.8
  877.98    44.9   938.9   42.93  1088.6   41.91 1131.63    42.2 1161.75   44.26
#Mann= 3 ,-1 , 0
       0     .08       0  408.01     .06       0  557.61     .08       0
Bank Sta=422.97,555.97
XS Rating Curve= 0
Exp/Cntr=.5,.3

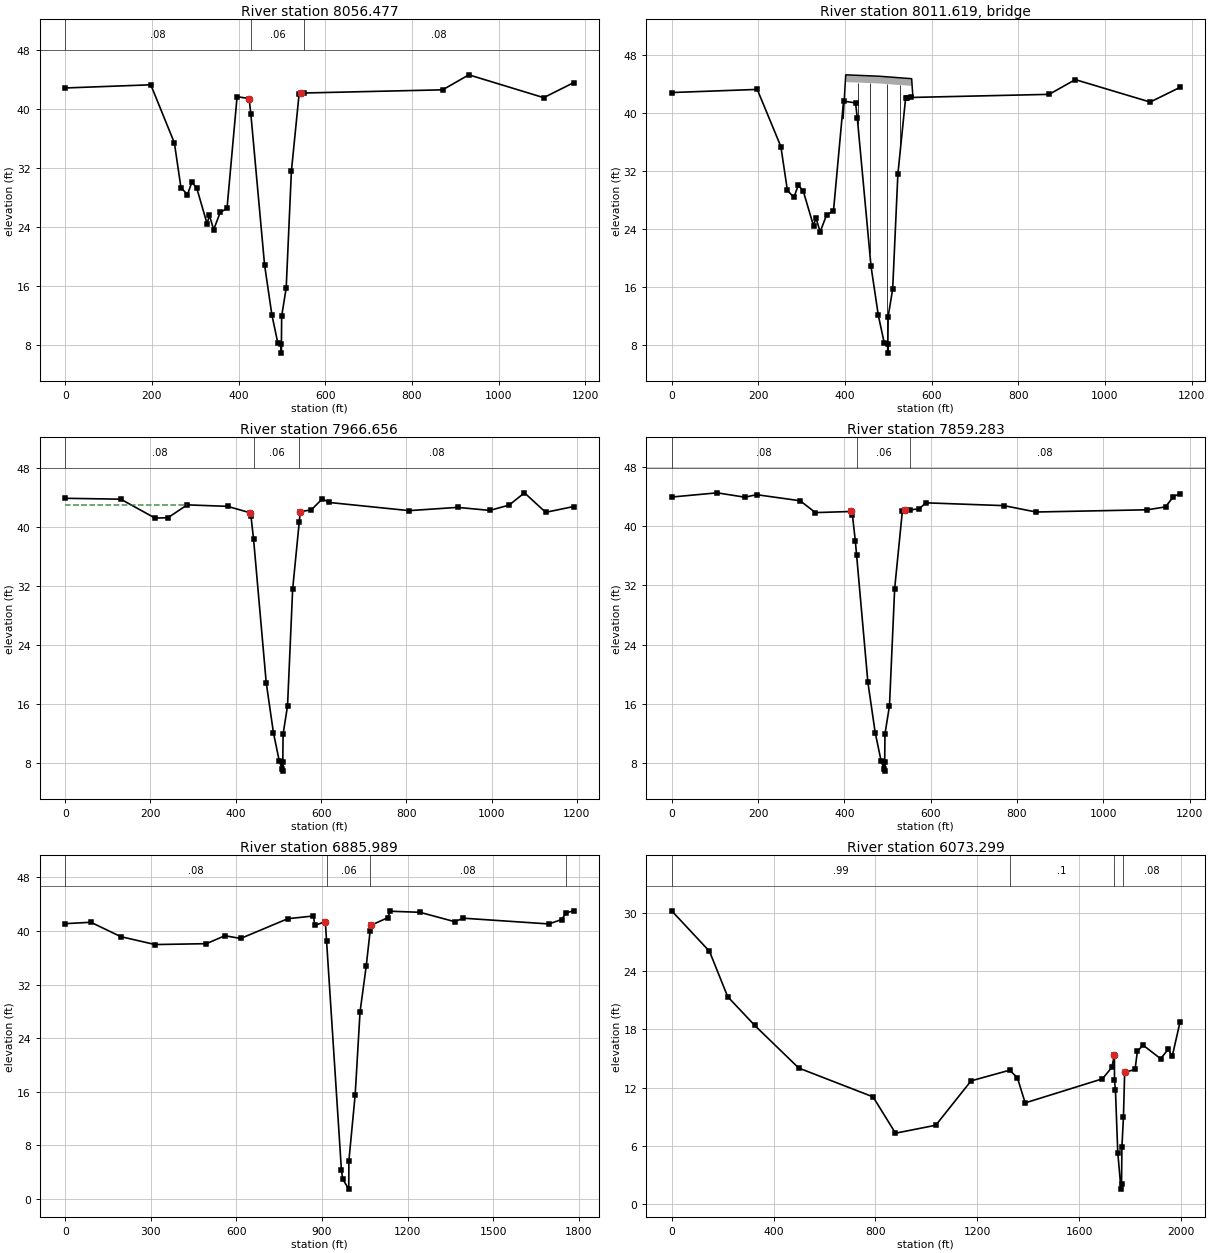
Type RM Length L Ch R = 1 ,8056.477,84.64,89.6,84.56
BEGIN DESCRIPTION:
1.0 Kinder Morgan Pipe Bridge XS 3
Stations 420.58-546.25 developed from survey information, and the remainder developed from LiDAR
END DESCRIPTION:
XS GIS Cut Line= 2
     3200467.785    13879113.549 3200332.887021913877948.2535761
#Sta/Elev= 30
       0   42.81   197.5   43.24  251.97   35.37  267.07   29.33  282.17   28.36
  292.23   30.06  303.64   29.24  327.47   24.42  332.83   25.57  342.57   23.62
  357.67   25.96  373.43   26.51  396.64   41.63  424.36   41.38  428.37   39.31
  460.03   18.88  476.95    12.1  490.79    8.24   498.6    8.11  498.67    6.91
  499.57   11.93  509.99   15.73  522.03   31.57  539.88   42.04   543.5   42.09
  551.32   42.13  871.08   42.56  931.48   44.59 1104.24    41.5 1173.08   43.52
#Mann= 3 ,-1 , 0
       0     .08       0  428.37     .06       0  551.32     .08       0
#XS Ineff= 1 ,-1
  203.23  396.64   41.63
Permanent Ineff=
       F
Bank Sta=424.36,543.5
XS Rating Curve= 0
Exp/Cntr=.5,.3

Type RM Length L Ch R = 3 ,8011.619,,,
BEGIN DESCRIPTION:
S7 Pipe 1.0 Kinder Morgan
(two pipes, the largest one was modeled)
END DESCRIPTION:
Bridge Culvert--1,0,-1,-1, 0
Deck Dist Width WeirC Skew NumUp NumDn MinLoCord MaxHiCord MaxSubmerge Is_Ogee
27,1,2.6,0, 5, 5, , , .95, 0, 0,0,,
  395.65  401.65  478.58  553.87  556.52
   39.25   45.25   45.06   44.72   42.31
   38.25   44.25   44.06   43.72   41.31
  395.65  401.65  478.58  553.87  556.52
   39.25   45.25   45.06   44.72   42.31
   38.25   44.25   44.06   43.72   41.31
Pier Skew, UpSta & Num, DnSta & Num=  ,429.61, 2 ,429.61, 2 , 0 , 0 , 0 ,,
    1.35    1.35
   36.03   44.25
    1.35    1.35
   36.03   44.25
Pier Skew, UpSta & Num, DnSta & Num=  ,457.3, 2 ,457.27, 2 , 0 , 0 , 0 ,,
    1.35    1.35
    15.7   44.25
    1.35    1.35
    15.7   44.25
Pier Skew, UpSta & Num, DnSta & Num=  ,496.88, 2 ,496.88, 2 , 0 , 0 , 0 ,,
    1.35    1.35
     8.7   44.25
    1.35    1.35
     8.7   44.25
Pier Skew, UpSta & Num, DnSta & Num=  ,527.26, 2 ,527.26, 2 , 0 , 0 , 0 ,,
    1.35    1.35
   36.29   44.25
    1.35    1.35
   36.29   44.25
BR Coef=-1 , 1 , 1 ,1.25, 0 ,,,.8,0,2,0,
WSPro=,,,, 1 ,,,, 0 ,,,, 0 ,,,,-1 ,-1 ,-1 , 0 , 0 , 0 , 0 , 0
BC Design=,, 0 ,, 0 ,,,,,,
BC HTab HWMax=44.59

Type RM Length L Ch R = 1 ,7966.656,102.94,107.13,102.83
BEGIN DESCRIPTION:
1.0 Kinder Morgan Pipe Bridge XS 2
Stations 431.95-557.62 developed from survey information, and the remainder developed from LiDAR
END DESCRIPTION:
XS GIS Cut Line= 2
     3200553.764    13879132.357 3200416.688010513877948.2471595
#Sta/Elev= 30
       0   43.84  130.17   43.72  210.51   41.17  240.71    41.2  286.01   42.95
  380.86   42.75  432.39    41.9  435.62   41.44  441.76   38.27   471.4   18.88
  488.32    12.1  502.16    8.24  508.49    7.26  509.98    8.11  510.05    6.91
  510.94   11.93  521.36   15.73   533.4   31.57  548.85   40.64  551.25   42.04
   577.1   42.27  603.11   43.78  618.21   43.28  806.31   42.17  920.21   42.61
  995.78    42.2 1041.02   42.92 1076.98   44.58 1126.77   41.94 1192.02   42.72
#Mann= 3 ,-1 , 0
       0     .08       0  441.76     .06       0  548.85     .08       0
#XS Ineff= 2 , 0
           286.6   42.99
Permanent Ineff=
       F       F
Bank Sta=432.39,551.25
XS Rating Curve= 0
Exp/Cntr=.5,.3

Type RM Length L Ch R = 1 ,7859.283,909,972.88,963.88
BEGIN DESCRIPTION:
Stations 415.12-540.79 developed from survey information, and the remainder developed from LiDAR
XS 1
END DESCRIPTION:
XS GIS Cut Line= 2
     3200657.476     13879147.94  3200522.06975313877978.2548528
#Sta/Elev= 30
       0   43.92  105.39   44.49   169.6    43.9  196.67   44.24  297.61   43.42
  332.92   41.82  415.12   41.97  418.79   41.44  425.41   38.02  428.37   36.08
  454.57   18.88  471.49    12.1  485.33    8.24  491.66    7.26  493.14    8.11
  493.22    6.91  494.11   11.93  504.53   15.73  516.57   31.57  534.42   42.04
  539.48   42.11  552.35   42.19   573.5   42.33   588.6   43.14   769.8   42.76
  844.07    41.9    1102    42.2 1144.01   42.59  1162.4   43.99  1177.5   44.37
#Mann= 3 ,-1 , 0
       0     .08       0  428.37     .06       0  552.35     .08       0
Bank Sta=415.12,539.48
XS Rating Curve= 0
Exp/Cntr=.3,.1

Type RM Length L Ch R = 1 ,6885.989,742.51,812.12,823.12
BEGIN DESCRIPTION:
Stations 874.89-1129.85 developed from survey information, and the remainder developed from LiDAR
END DESCRIPTION:
XS GIS Cut Line= 2
     3201544.196    13879718.121 3201527.175745313877936.7492159
#Sta/Elev= 30
       0   41.09   89.88    41.3  194.88   39.15  314.89   37.97   494.9    38.1
  559.56   39.29   614.9   38.88  779.91   41.83  869.91   42.24  874.89   40.82
  911.53   41.41  915.87   38.56  968.02    4.28  972.64    2.91  993.71    1.42
  994.18    5.65 1016.24   15.52 1033.26   27.89 1054.94   34.75 1068.52   39.96
 1070.83   40.84 1129.85   41.97 1139.05   42.95 1243.06   42.79 1364.94   41.39
 1394.94   41.91 1694.95   41.05 1739.95   41.71 1755.43   42.71 1781.45   43.01
#Mann= 4 ,-1 , 0
       0     .08       0  915.87     .06       0 1068.52     .08       0
 1755.43      .1       0
Bank Sta=911.53,1070.83
XS Rating Curve= 0
Exp/Cntr=.3,.1

Type RM Length L Ch R = 1 ,6073.299,613.33,587.96,559.14
BEGIN DESCRIPTION:
Stations 1728.05-1819.57 developed from survey information, and the remainder developed from LiDAR
Roughness coefficients were increased to simulate the swamp area near the San Jacinto River
END DESCRIPTION:
XS GIS Cut Line= 4
     3202056.357    13880445.707     3202308.663    13878775.903
     3202339.523    13878603.251 3202359.464198713878472.9754662
#Sta/Elev= 30
       0    30.2  148.48   26.03  219.92   21.36  326.12    18.4  498.91   14.01
  790.73   11.04  878.85     7.3    1037    8.12 1175.66   12.69 1327.36   13.79
  1357.7      13 1388.04   10.42 1691.46    12.9 1728.05   14.07 1738.55   15.32
  1738.8   12.73 1742.49   11.76 1751.65    5.31 1764.27    1.54 1766.43    2.05
 1767.96    5.91 1773.89    8.92 1778.68   13.56 1819.57   13.87  1828.6   15.74
 1850.94   16.37 1919.79   14.97 1950.14   15.95 1965.32    15.2 1995.94   18.73
#Mann= 4 ,-1 , 0
       0     .99       0 1327.36      .1       0 1738.55     .06       0
 1773.89     .08       0
Bank Sta=1738.55,1778.68
XS Rating Curve= 0
Exp/Cntr=.3,.1