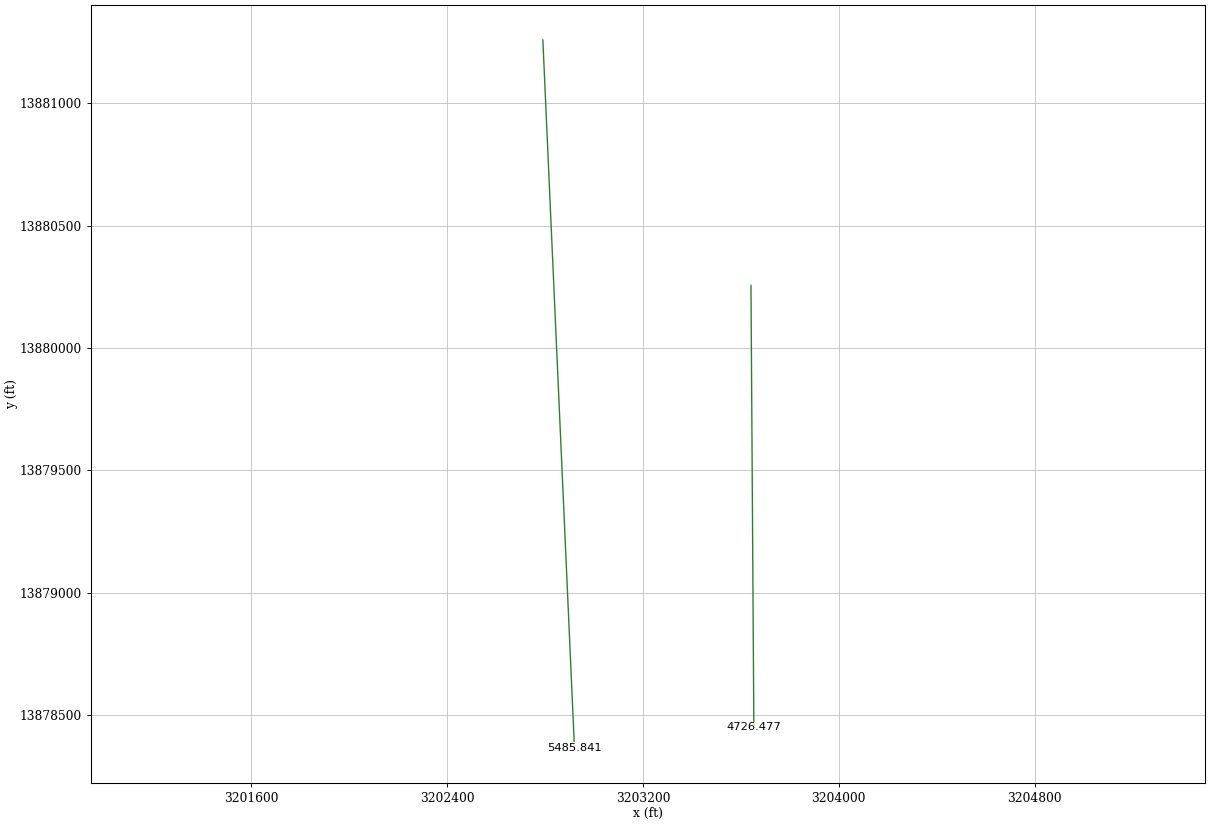
HEC-RAS study G103-07-00.prj: G103-07-00

--- G103-07-00.g01 (geometry) --- (continued)

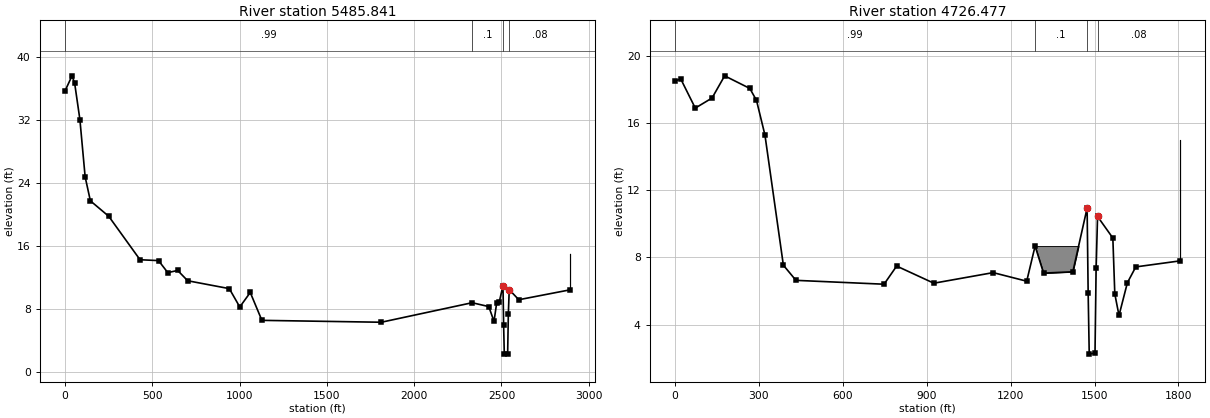
Type RM Length L Ch R = 1 ,5485.841,756.65,759.81,739.28
BEGIN DESCRIPTION:
Stations 2503.94 - 2599.32 developed from survey information, and the remainder developed from LiDAR.
Blocked obstruction placed at drainage boundary
Roughness coefficients were increased to simulate the swamp area near the San Jacinto River
END DESCRIPTION:
XS GIS Cut Line= 2
     3202790.955    13881258.237     3202919.954    13878367.486
#Sta/Elev= 30
       0   35.69   40.03    37.6   55.04   36.66   85.07   32.05   115.1   24.77
  145.13   21.72  250.24   19.76  429.51   14.24  535.52   14.13  588.58    12.6
  645.11   12.88   702.6   11.57  940.93   10.57 1000.99    8.24 1061.05   10.08
  1127.6    6.54 1811.79     6.3 2331.95    8.78  2427.4    8.29 2457.43    6.41
 2472.45    8.72 2487.46    8.88 2508.81   10.94 2512.51    5.89 2516.34    2.25
 2535.52    2.32  2539.5    7.35 2544.58   10.44 2599.32    9.16 2893.63   10.42
#Mann= 4 ,-1 , 0
       0     .99       0 2331.95      .1       0 2508.81     .06       0
 2544.58     .08       0
#Block Obstruct= 1 ,-1
    2892 2893.63      15
Bank Sta=2508.81,2544.58
XS Rating Curve= 0
Exp/Cntr=.3,.1

Type RM Length L Ch R = 1 ,4726.477,4698.62,4728.48,4760.29
BEGIN DESCRIPTION:
Stations 2503.94 - 2599.32 developed from survey information, and the remainder developed from LiDAR
Copied survey points from previous section (5485.841).
Blocked obstruction placed at drainage boundary
Roughness coefficients were increased to simulate the swamp area near the San Jacinto River
Blocked obstruction was placed on the left side of the channel to model the existing detention pond in that area.
END DESCRIPTION:
XS GIS Cut Line= 2
     3203641.175    13880255.562     3203652.902    13878449.576
#Sta/Elev= 30
       0    18.5    20.2   18.63   72.32   16.89  132.32   17.49  177.32   18.81
  267.32   18.06   291.2   17.35  321.39   15.29  387.32    7.54  432.32    6.64
  747.33    6.41  792.33    7.49  925.33    6.47 1137.34     7.1 1257.34    6.59
 1287.34    8.68 1317.61    7.07 1422.34    7.15 1473.32   10.94 1477.06    5.89
 1480.92    2.25 1501.54    2.32 1505.56    7.35 1510.66   10.44 1565.33    9.16
 1572.35    5.83 1587.35    4.55 1617.35     6.5 1647.35    7.44 1806.02     7.8
#Mann= 4 ,-1 , 0
       0     .99       0 1287.34      .1       0 1473.32     .06       0
 1510.66     .08       0
#Block Obstruct= 2 ,-1
    1805 1806.02      15 1287.34 1473.32    8.68
Bank Sta=1473.32,1510.66
XS Rating Curve= 0
Exp/Cntr=.3,.1

Chan Stop Cuts=-1